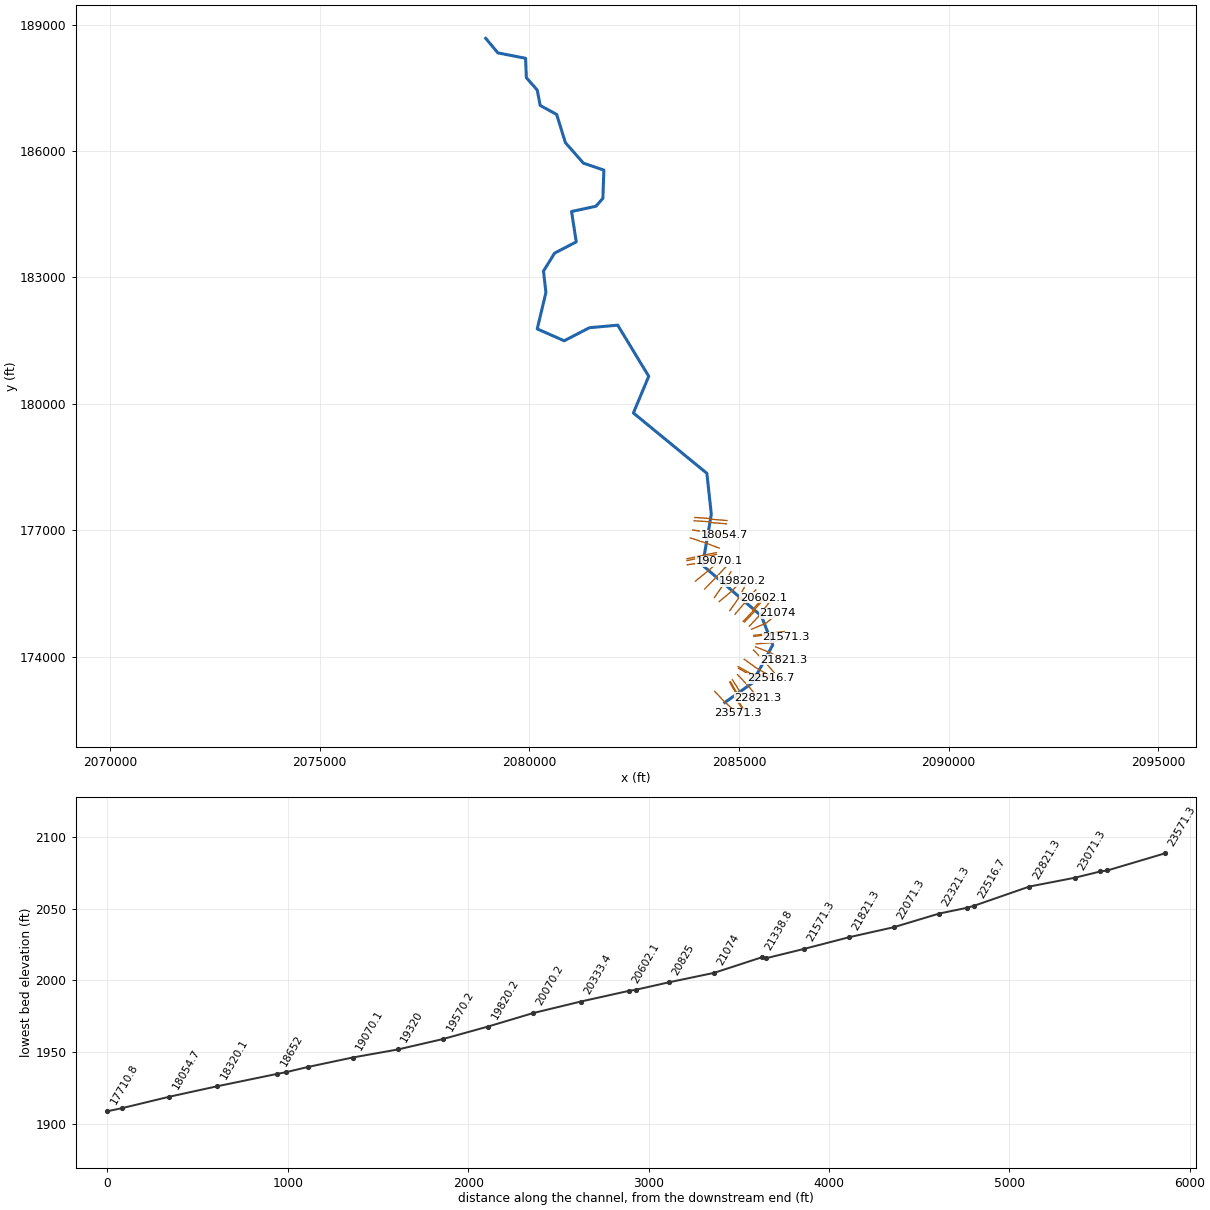
--- RCKCMPCK.prj (project) ---

Proj Title=RCKCMPCK
Current Plan=p01
Default Exp/Contr=0,0
English Units
Geom File=g01
Flow File=f01
Plan File=p01
BEGIN DESCRIPTION:
END DESCRIPTION:
DSS Export Rating Curves= 0
DSS Export Rating Curve Sorted= 0
DSS Export Volume Flow Curves= 0
DXF OffsetX= 0
DXF OffsetY= 0
DXF ScaleX= 0
DXF ScaleY= 0

--- RCKCMPCK.p01 (plan) ---

Plan Title=Floodplain
Program Version=4.00
Geom File=g01
Flow File=f01
K Sum by GR=0
Std Step Tol=0.01
Critical Tol=0.01
Num of Std Step Trials=20
Max Error Tol=0.3
Flow Tol Ratio=0.001
Split Flow NTrial=30
Split Flow Tol=0.02
Split Flow Ratio=0.02
Log Output Level=0
Friction Slope Method=1
Unsteady Friction Slope Method=2
Unsteady Bridges Friction Slope Method=1
Global Log Level=0
CheckData=False
Run HTab=0
Run UNet=0
Run PostProcess=0
UNET Theta=0
UNET Theta Warmup=0
UNET ZTol=0
UNET ZSATol=0
UNET MxIter=0
UNET MaxInSteps=0
UNET DtIC=0
UNET DtMin=0
UNET MaxCRTS=0
UNET WFStab=0
UNET SFStab=0
UNET WFX=0
UNET SFX=0
UNET DSS MLevel=0
UNET DZMax Abort=0
UNET Convert EG Bridges=0
UNET Use Existing IB Tables=0
UNET Froude Limit=0
UNET Froude Power=0
Write IC File=0
Echo Input=False
Echo Output=False
Write Detailed=0

--- RCKCMPCK.f01 (steady flow) ---

Flow Title=2010 USGS WV Regression Equation
Program Version=4.00
Number of Profiles=1
Profile Names=P100yr
River Rch & RM=RCKCMPCK,Main      ,23571.3
534.2733
River Rch & RM=RCKCMPCK,Main      ,22516.7
560.7513
River Rch & RM=RCKCMPCK,Main      ,22477.8
638.0585
River Rch & RM=RCKCMPCK,Main      ,20070.2
655.2482
River Rch & RM=RCKCMPCK,Main      ,19570.2
956.1445
River Rch & RM=RCKCMPCK,Main      ,17061.8
1002.379
River Rch & RM=RCKCMPCK,Main      ,16570.1
1387.525
River Rch & RM=RCKCMPCK,Main      ,14841.7
1400.380
River Rch & RM=RCKCMPCK,Main      ,14518.2
1602.749
River Rch & RM=RCKCMPCK,Main      ,11810.4
1625.077
River Rch & RM=RCKCMPCK,Main      ,11545.2
3458.882
River Rch & RM=RCKCMPCK,Main      ,525.5
3726.601
River Rch & RM=RCKCMPCK,Main      ,100.5
3727.190
Boundary for River Rch & Prof#=RCKCMPCK,Main      ,1
Up Type=0
Dn Type=3
Dn Slope=0.009032

--- RCKCMPCK.g01 (geometry) ---

Geom Title=LiDAR
Program Version=4.10

River Reach=RCKCMPCK        ,Main
Reach XY= 30
     2084661.471      172905.629     2085317.058      173368.331
     2085808.013      174277.007      2085534.13      174964.165
     2084133.424      176166.649     2084341.758      177380.017
     2084235.855      178349.635     2082483.303      179782.275
     2082849.072      180654.091     2082109.156      181868.244
     2081434.387      181807.449     2080832.078      181497.143
     2080189.596      181779.671     2080397.061      182644.255
     2080338.772      183151.372     2080603.658      183578.283
     2081120.151      183845.644     2081008.172      184566.998
     2081589.769      184691.997     2081755.568      184880.366
     2081779.005      185549.637     2081292.026      185714.567
     2080861.471      186201.546     2080653.137      186871.685
     2080259.908      187085.227     2080189.292      187451.633
     2079929.892      187745.089     2079911.644      188205.192
     2079251.228      188333.317     2078961.618      188679.158

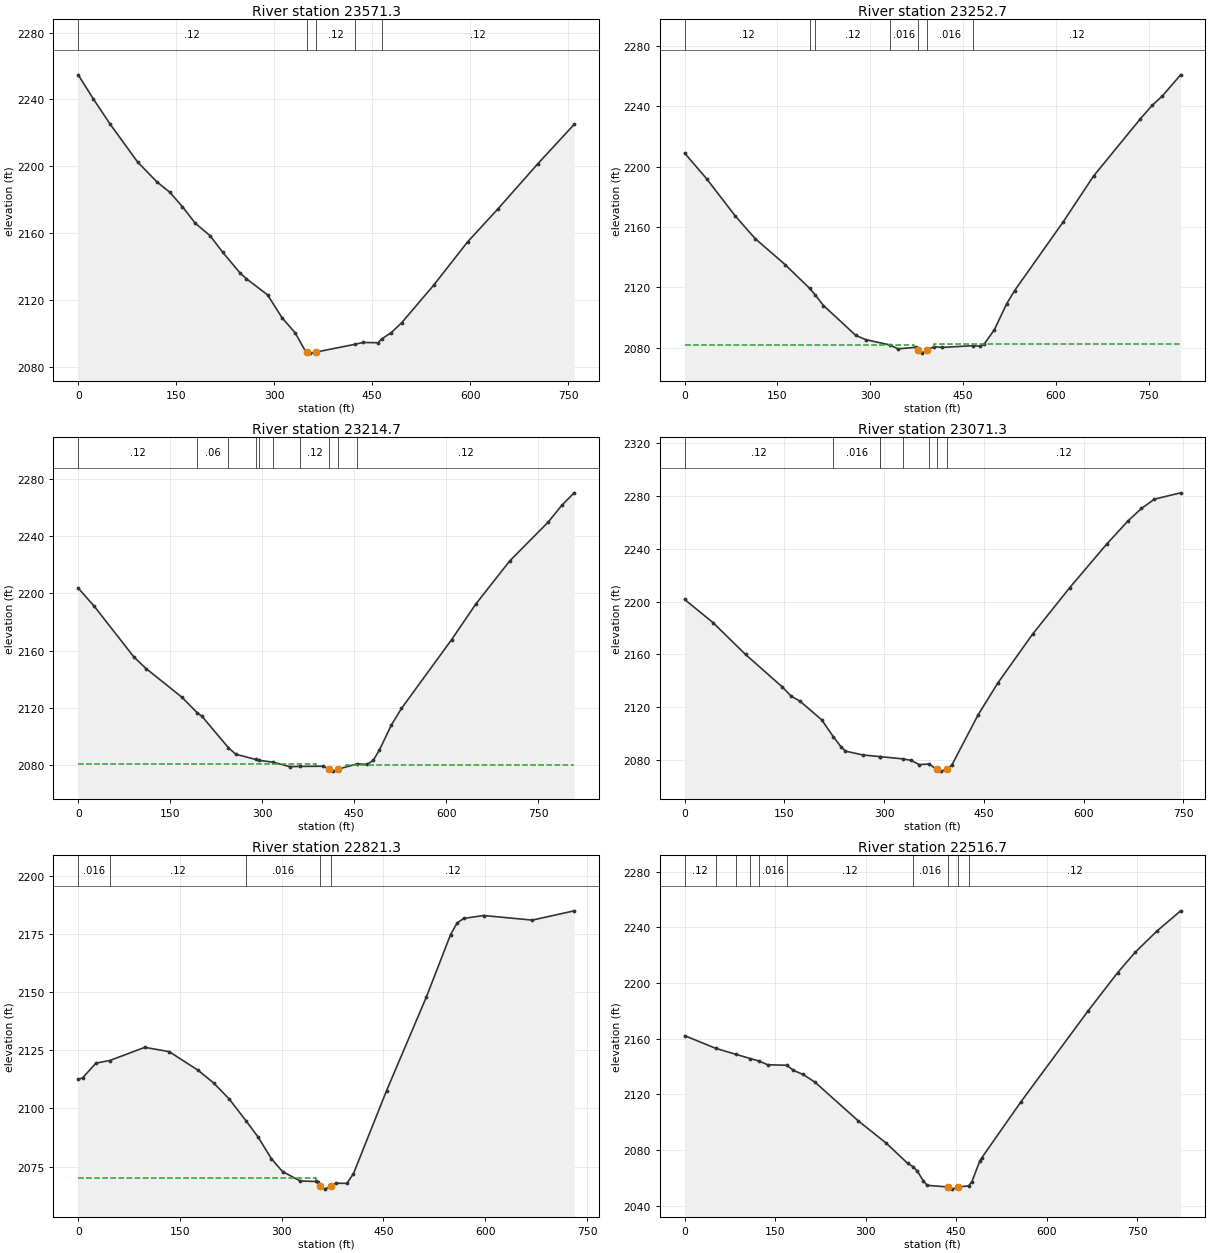
Type RM Length L Ch R = 1 ,23571.3 ,361.3,318.6,270.4
XS GIS Cut Line= 3
     2084422.787      173172.343     2084668.738      172912.187
     2084971.707      172649.434
#Sta/Elev= 30
       0 2254.72    22.8 2240.51    48.8 2225.27    91.1  2202.5   120.4 2190.72
     140 2184.55   159.5 2175.88     179 2166.06   201.8 2158.49   221.3 2148.56
   247.4 2136.34   257.1 2132.89   289.7 2123.16   312.4 2109.23     332 2100.44
   348.2 2089.16  349.43 2088.85   354.8  2088.3   364.5 2088.98  423.122093.543
   436.3 2094.68   459.1 2094.51  464.222096.733   478.6 2100.41     495 2106.44
   543.9 2128.88     596 2154.86   641.7 2174.27   703.6 2201.64     759 2225.06
#Mann= 5 ,-1 , 0
       0     .12       0  349.43    .045       0   364.5     .12       0
  423.12    .016       0  464.22     .12       0
Bank Sta=349.43,364.5
XS Rating Curve= 0 ,0
Exp/Cntr=0.3,0.1

Type RM Length L Ch R = 1 ,23252.7 ,44.7,38,39
XS GIS Cut Line= 4
     2084778.356      173393.927     2084948.929      173094.448
      2084881.22      173056.688     2085094.762      172742.886
#Sta/Elev= 30
       0 2208.97    35.8 2191.86    81.3 2167.59   113.8  2152.4   162.6 2135.02
  201.862119.441  210.972115.025   224.4 2107.98   276.4 2088.24   292.6 2085.37
  331.54 2081.88   344.6 2079.29   373.7 2080.25  377.812078.367   383.4 2076.43
  391.722078.389   402.8 2080.75   415.7  2080.2  465.532081.363   477.8 2081.05
   484.4  2082.6   500.7    2092   520.3    2109   533.4 2117.92     612  2163.5
     661 2193.83   736.3 2231.57   755.9 2240.74   772.3 2246.93   801.7  2260.9
#Mann= 7 ,-1 , 0
       0     .12       0  201.86     .06       0  210.97     .12       0
  331.54    .016       0  377.81    .045       0  391.72    .016       0
  465.53     .12       0
#XS Ineff= 2 , 0
          371.01 2081.76  403.83         2082.16
Permanent Ineff=
       F       F
Bank Sta=377.81,391.72
XS Rating Curve= 0 ,0
Exp/Cntr=0.3,0.1

Type RM Length L Ch R = 1 ,23214.7 ,96.4,143.4,189.7
XS GIS Cut Line= 4
     2084800.088      173398.493     2084983.955      173076.436
     2084916.247      173038.676     2085119.098      172740.941
#Sta/Elev= 30
       0 2203.78      26 2191.15    91.1 2155.43   110.6 2147.51   169.2  2127.4
  193.972116.603   201.7 2114.16   244.92092.103     257 2087.55  289.362083.934
  295.162083.287  317.552082.006   344.8 2078.91  361.652079.044   399.9 2079.19
   409.1 2077.13   416.1 2075.75   424.1 2077.19  454.982080.828   471.3 2080.44
   481.1 2083.39     491 2090.44   510.6 2108.02     527 2119.56   608.9 2167.78
   648.2 2192.59   703.8  2222.9   766.1 2249.88     789 2261.93   808.6 2270.41
#Mann= 10 ,-1 , 0
       0     .12       0  193.97     .06       0   244.9     .12       0
  289.36     .08       0  295.16     .12       0  317.55    .016       0
  361.65     .12       0   409.1    .045       0   424.1    .016       0
  454.98     .12       0
#XS Ineff= 2 , 0
          387.89 2080.63  436.15         2080.36
Permanent Ineff=
       F       F
Bank Sta=409.1,424.1
XS Rating Curve= 0 ,0
Exp/Cntr=0.3,0.1

Type RM Length L Ch R = 1 ,23071.3 ,244.9,250,243.5
XS GIS Cut Line= 3
     2084844.119      173448.688     2085051.736      173123.547
     2085346.972        172917.1
#Sta/Elev= 30
       0 2201.57    42.5 2184.08    91.5 2159.89   147.1  2135.1   160.2 2128.19
   173.3 2124.49     206 2110.33  223.492097.543   235.4 2089.64   241.9 2086.55
   268.1  2083.6  293.582082.381  294.53 2082.32  328.632080.626     340 2079.57
   353.1 2076.27  368.012076.772   379.2  2072.6   385.8 2071.35  394.242072.703
   402.2 2076.27   441.4 2114.07   470.9 2138.11   523.3 2175.26     579 2210.44
   634.7 2243.55   667.4 2261.48   687.1 2270.65   706.7 2277.71     746  2282.5
#Mann= 8 ,-1 , 0
       0     .12       0  223.49    .016       0  293.58     .08       0
  294.53     .12       0  328.63    .016       0  368.01     .12       0
   379.2    .045       0  394.24     .12       0
Bank Sta=379.2,394.24
XS Rating Curve= 0 ,0
Exp/Cntr=0.3,0.1

Type RM Length L Ch R = 1 ,22821.3 ,286.5,304.6,323.8
XS GIS Cut Line= 3
     2084968.261       173568.94     2085219.638      173306.514
     2085450.631      173020.404
#Sta/Elev= 30
       0 2112.44     6.6 2113.15    26.2 2119.44   46.352120.538    98.2 2126.21
   134.2 2124.35   176.8 2116.35   199.7 2110.89   222.6 2104.01  247.312094.676
   265.2 2087.67   284.8 2078.32   301.2 2072.83   327.4 2068.78   350.3 2068.56
   353.6 2068.13   356.8 2066.56   363.4 2065.28   373.2 2066.66   379.7 2067.83
   395.9 2067.74   405.7 2071.89   454.5 2107.56   513.1 2147.75   548.9 2174.66
   558.6 2179.67   568.4 2181.63   597.7 2182.87   669.3 2180.89   731.1 2184.88
#Mann= 5 ,-1 , 0
       0    .016       0   46.35     .12       0  247.31    .016       0
   356.8    .045       0   373.2     .12       0
#XS Ineff= 2 , 0
          349.99 2069.94
Permanent Ineff=
       F       F
Bank Sta=356.8,373.2
XS Rating Curve= 0 ,0
Exp/Cntr=0.3,0.1

Type RM Length L Ch R = 1 ,22516.7 ,39,38.9,39
XS GIS Cut Line= 4
      2084986.98      173720.672     2085307.813      173543.589
     2085446.702      173540.117     2085757.813      173480.394
#Sta/Elev= 30
       0 2162.24   51.582153.119   85.322148.794  108.772145.816  123.362144.017
   137.4 2141.36  169.722140.955     180 2137.39   196.3 2134.36     216 2128.85
   287.9    2101   333.7  2085.2   369.7 2070.54  378.692068.131   385.8 2064.93
   395.5 2057.93     402 2054.74  436.272053.573     444 2052.01   453.7 2053.57
  470.722054.353   476.3 2057.46   489.2  2072.2   492.5 2074.51   557.6 2114.81
   668.7 2179.98   717.7 2207.47   747.1 2222.23     783  2237.4   822.2 2251.91
#Mann= 10 ,-1 , 0
       0     .12       0   51.58     .08       0   85.32    .016       0
  108.77     .08       0  123.36    .016       0  169.72     .12       0
  378.69    .016       0  436.27    .045       0   453.7    .016       0
  470.72     .12       0
Bank Sta=436.27,453.7
XS Rating Curve= 0 ,0
Exp/Cntr=0.3,0.1

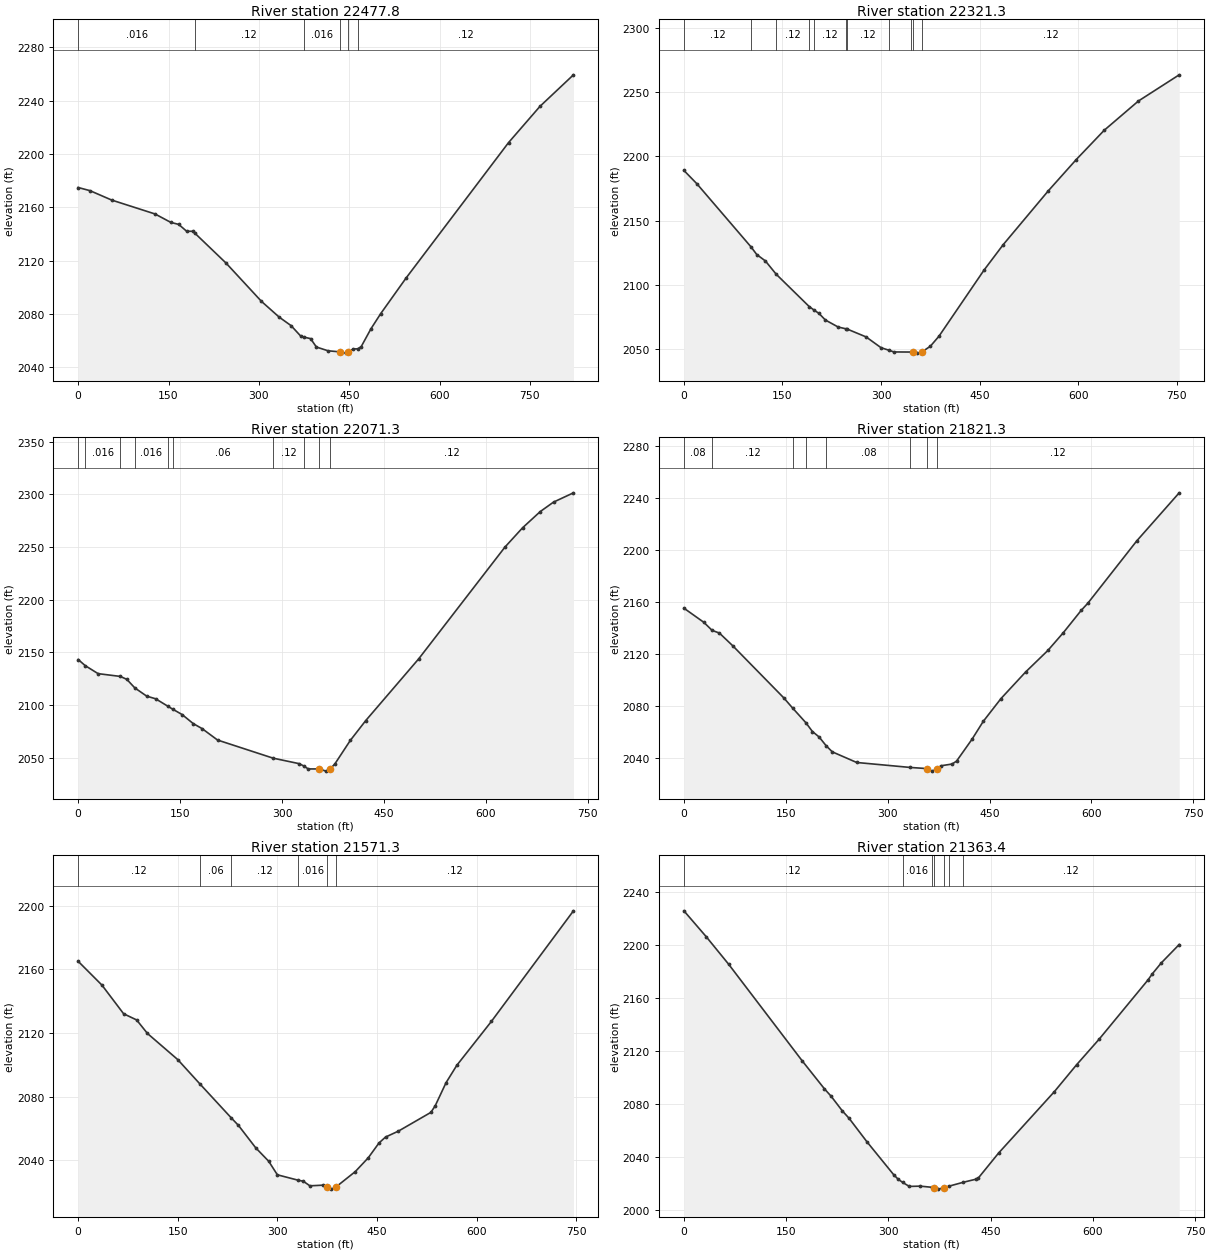
Type RM Length L Ch R = 1 ,22477.8 ,169.5,156.5,144.7
XS GIS Cut Line= 4
     2084982.813      173759.561     2085303.647      173582.478
     2085442.536      173579.005     2085753.647      173519.283
#Sta/Elev= 30
       0 2174.83    19.6 2172.47    55.6 2165.42   127.6 2154.98   153.8 2148.66
   166.9 2147.15     180 2142.04   189.8 2141.98  193.912140.482   245.4 2118.17
   304.3 2089.39   333.7 2077.58   353.4 2071.21   369.7 2063.23  374.352062.635
   385.8 2061.44   395.5 2055.13   414.9 2052.32   434.3 2051.53     444 2050.57
  448.662051.495   456.9 2053.72     4642053.769   469.8 2055.42     486 2068.82
   502.2 2080.19   544.6 2107.08   714.4  2208.5   766.7 2235.76   822.2 2259.38
#Mann= 6 ,-1 , 0
       0    .016       0  193.91     .12       0  374.35    .016       0
   434.3    .045       0  448.66    .016       0     464     .12       0
Bank Sta=434.3,448.66
XS Rating Curve= 0 ,0
Exp/Cntr=0.3,0.1

Type RM Length L Ch R = 1 ,22321.3 ,253.1,250,241.5
XS GIS Cut Line= 3
     2085126.023      173935.433     2085417.665      173726.445
     2085759.059      173527.646
#Sta/Elev= 30
       0 2189.05    19.6 2178.74  102.212129.354   110.9 2123.42     124 2118.45
   140.52108.053  190.722082.836   198.12080.085   205.5 2077.53   215.3 2072.35
   234.8 2066.87  246.172065.536  247.892065.411   277.2 2059.18   300.1 2050.72
  312.132048.758   319.6 2047.43  345.442047.361     349 2047.11   355.5 2046.51
   362.1  2047.4   375.1 2051.89   388.2 2059.71   456.7 2111.25   486.1 2131.24
   554.7 2173.22   597.1 2197.54   639.6 2220.36   691.8 2243.26   753.8 2263.67
#Mann= 11 ,-1 , 0
       0     .12       0  102.21    .016       0   140.5     .12       0
  190.72     .08       0   198.1     .12       0  246.17    .016       0
  247.89     .12       0  312.13    .016       0  345.44     .12       0
     349    .045       0   362.1     .12       0
Bank Sta=349,362.1
XS Rating Curve= 0 ,0
Exp/Cntr=0.3,0.1

Type RM Length L Ch R = 1 ,22071.3 ,240.2,250,258.1
XS GIS Cut Line= 3
     2085349.583      174153.464     2085601.671      173889.924
     2085842.663      173616.846
#Sta/Elev= 30
       0 2143.09   10.342137.267    29.3 2129.66    62.12127.021    71.6 2124.22
   83.352116.121   100.9 2108.27     114 2105.79  132.242098.605  138.992095.958
     153  2090.8   169.3 2082.23   182.4 2077.45   205.1 2066.61  286.752049.418
   325.6 2044.12  331.972041.953   338.6 2039.17   354.9 2039.14   364.7 2037.08
  370.112038.714   377.7 2043.86   400.5 2066.25   423.2 2085.08   501.3 2143.84
   628.1 2249.86   654.1 2268.23   680.1 2283.62   699.6 2292.57   728.9 2301.38
#Mann= 10 ,-1 , 0
       0     .12       0   10.34    .016       0    62.1     .06       0
   83.35    .016       0  132.24     .12       0  138.99     .06       0
  286.75     .12       0  331.97    .016       0   354.9    .045       0
  370.11     .12       0
Bank Sta=354.9,370.11
XS Rating Curve= 0 ,0
Exp/Cntr=0.3,0.1

Type RM Length L Ch R = 1 ,21821.3 ,239.1,250,269.6
XS GIS Cut Line= 3
      2085396.79      174230.196     2085736.714      174096.394
      2086058.25      173926.123
#Sta/Elev= 30
       0 2155.42    29.4  2144.5   41.552138.302    52.2 2136.29    71.8 2126.54
   146.8 2086.53   160.12078.542  179.492067.329   189.2 2060.52     199 2056.35
  209.622049.443   218.5 2044.86   254.4 2036.69  333.422032.864   357.8    2032
   365.3 2030.04   371.9 2031.58   378.4 2034.15   394.8  2035.5   401.4 2037.73
   424.3 2054.66   440.7  2068.3   466.9 2085.91     503 2106.26   535.8 2122.85
   558.7 2136.61   584.9  2153.7   594.8 2159.29   666.9 2207.29   729.2 2244.16
#Mann= 8 ,-1 , 0
       0     .08       0   41.55     .12       0   160.1     .06       0
  179.49     .12       0  209.62     .08       0  333.42    .016       0
   357.8    .045       0   371.9     .12       0
Bank Sta=357.8,371.9
XS Rating Curve= 0 ,0
Exp/Cntr=0.3,0.1

Type RM Length L Ch R = 1 ,21571.3 ,205.2,207.9,201.9
XS GIS Cut Line= 3
      2085410.69      174299.666       2085794.1      174329.134
      2086131.96      174456.296
#Sta/Elev= 30
       0    2165    35.8 2150.04    68.4 2132.06      88 2128.17   104.3 2119.67
   149.9 2103.26  183.182088.007   230.72066.522   241.2 2061.96   267.2 2047.87
   286.8 2039.41   299.8 2030.91  330.922027.527   338.9 2026.86   348.7 2023.99
   368.2 2024.39   374.8 2023.46   381.3 2021.91   387.8 2023.19   417.1 2032.92
   436.6 2041.57   452.8  2050.9   462.6  2054.6   482.1 2058.36   530.9 2070.12
   537.4 2074.25   553.7 2088.74   569.9 2099.66     622 2127.26   745.5 2196.71
#Mann= 6 ,-1 , 0
       0     .12       0  183.18     .06       0   230.7     .12       0
  330.92    .016       0   374.8    .045       0   387.8     .12       0
Bank Sta=374.8,387.8
XS Rating Curve= 0 ,0
Exp/Cntr=0.3,0.1

Type RM Length L Ch R = 1 ,21363.4 ,24.6,24.6,24.5
XS GIS Cut Line= 2
     2085359.897      174476.922      2086080.73      174569.283
#Sta/Elev= 30
       0 2225.71    32.7 2206.18    65.5 2185.46   173.5 2112.44   206.2 2091.26
     216 2085.67   232.4 2074.64   242.2  2069.1   268.4 2051.38   307.7 2026.47
   314.3 2023.02  320.912020.618   330.6 2017.58     347 2017.77  364.062016.895
   367.2 2016.38   373.2 2015.52   382.2  2016.6   389.42017.819  410.112020.724
   428.8 2023.06   432.1 2023.99   461.6 2042.69   543.4 2089.05   576.1 2109.42
   608.9 2128.55   680.9  2173.5   687.4 2178.21   700.5 2186.41   726.7 2200.26
#Mann= 7 ,-1 , 0
       0     .12       0  320.91    .016       0  364.06     .12       0
   367.2    .045       0   382.2     .12       0   389.4     .08       0
  410.11     .12       0
Bank Sta=367.2,382.2
XS Rating Curve= 0 ,0
Exp/Cntr=0.3,0.1

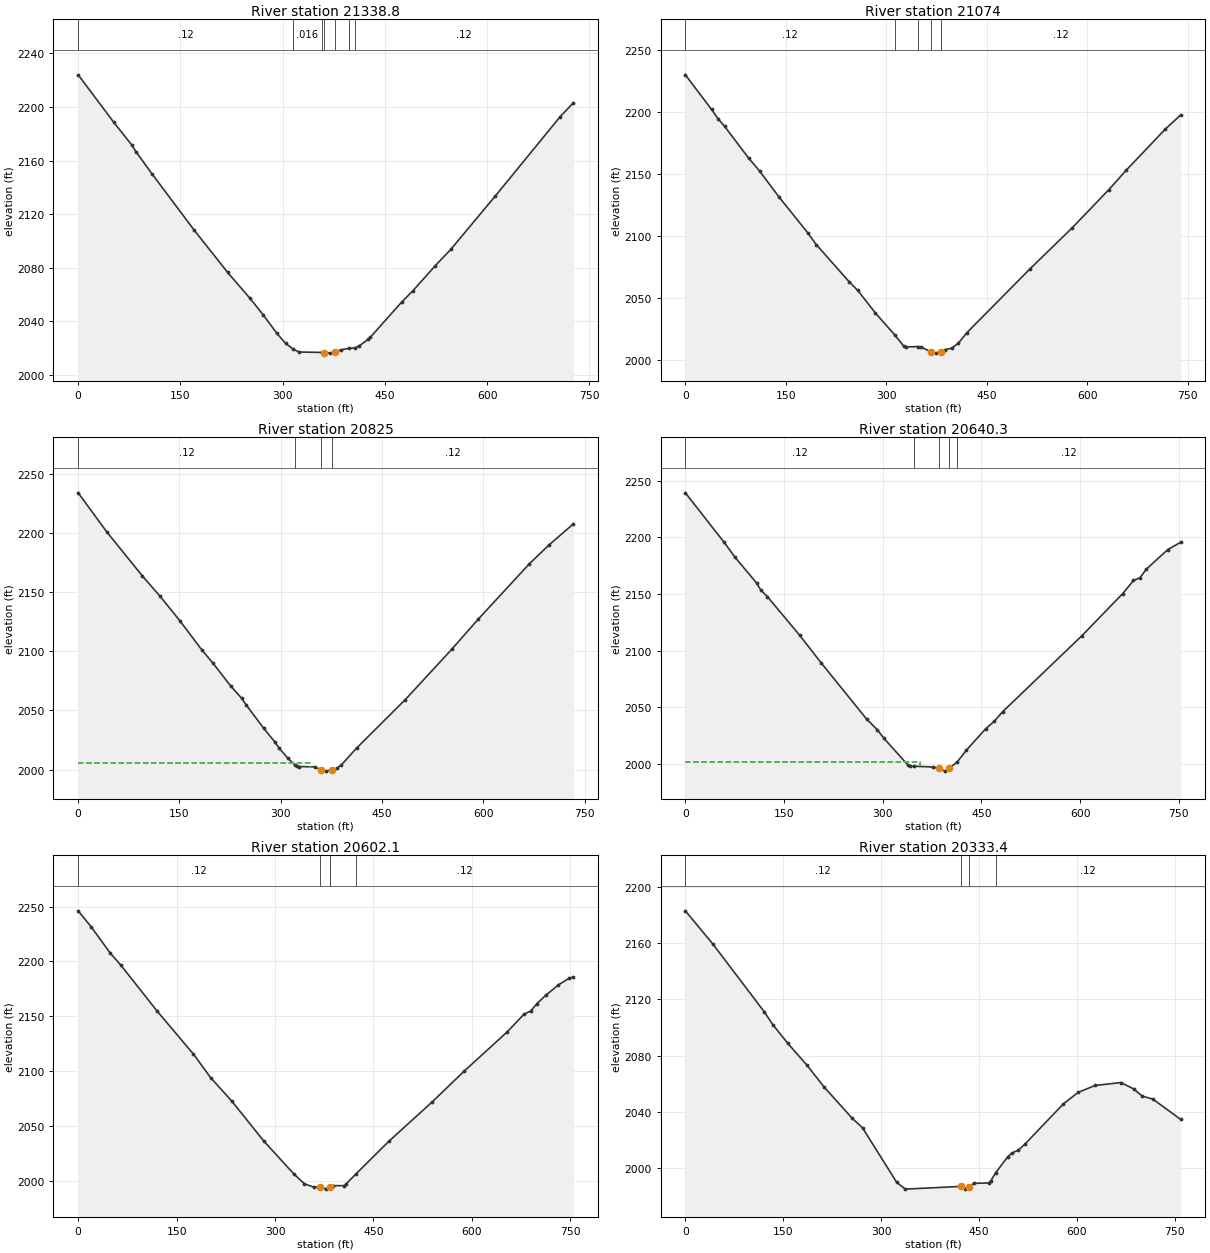
Type RM Length L Ch R = 1 ,21338.8 ,258,264.8,276
XS GIS Cut Line= 2
     2085357.119      174501.228     2086077.952      174593.589
#Sta/Elev= 30
       0 2224.04    52.4 2188.47    78.6 2171.66    85.1  2166.4     108 2150.27
   170.2 2108.02   219.3 2076.45   252.1 2057.08   271.7 2044.59   291.4 2031.03
   304.4  2023.4  315.182019.254   324.1 2016.97  357.642016.682   360.1 2016.57
   369.9 2016.15   376.5 2016.74   386.3 2018.72  397.352019.701  406.042020.081
   412.5 2021.61   425.6 2026.46   428.8 2028.09   474.7 2054.32     491 2062.66
   523.8  2081.4   546.7 2093.65   612.2 2133.63   707.1 2192.71   726.7 2203.21
#Mann= 7 ,-1 , 0
       0     .12       0  315.18    .016       0  357.64     .12       0
   360.1    .045       0   376.5     .12       0  397.35     .08       0
  406.04     .12       0
Bank Sta=360.1,376.5
XS Rating Curve= 0 ,0
Exp/Cntr=0.3,0.1

Type RM Length L Ch R = 1 ,21074   ,238.8,249,254.7
XS GIS Cut Line= 3
      2085300.31      174647.359     2085649.287      174791.956
     2085928.123      175021.964
#Sta/Elev= 30
       0 2229.94    39.1 2201.98    48.8 2194.46    58.6 2188.33    94.4 2162.75
   110.7 2152.37     140 2131.18   182.4  2102.6   195.4 2092.91   244.2 2063.09
   257.3 2055.94   283.3 2037.92  312.242020.179   325.6 2011.15   328.9 2010.34
  347.032010.586   351.7 2010.24  366.832006.317   374.5 2005.32     381 2006.46
   387.5 2008.12   397.3 2009.28   407.1 2013.11   420.1 2021.81   514.5 2073.42
   576.4 2105.92   631.8 2137.14   657.8 2152.85   716.4 2186.17   739.2 2197.54
#Mann= 5 ,-1 , 0
       0     .12       0  312.24    .016       0  347.03     .12       0
  366.83    .045       0     381     .12       0
Bank Sta=366.83,381
XS Rating Curve= 0 ,0
Exp/Cntr=0.3,0.1

Type RM Length L Ch R = 1 ,20825   ,152.4,184.6,181.1
XS GIS Cut Line= 3
     2085250.358      174720.279     2085503.368      174989.855
     2085719.727      175282.461
#Sta/Elev= 30
       0 2233.81    42.5 2200.72    94.9 2163.75   121.1  2146.6   150.5 2125.87
   183.2 2101.12   199.6 2089.99   225.8 2070.77   242.1 2060.38   248.6 2054.89
   274.8 2034.99   291.2 2023.46   297.7 2018.26   310.8  2009.5  320.692004.295
   323.9 2003.06   327.2 2002.69   350.1 2002.38   359.9 1999.85   366.4 1998.79
   376.3  1999.8   382.8  2001.2   389.4 2003.79   412.3  2018.2   484.5 2059.19
   553.3 2101.66   592.6 2127.15     668  2173.7   697.6 2189.93   733.6 2207.63
#Mann= 4 ,-1 , 0
       0     .12       0  320.69    .016       0   359.9    .045       0
   376.3     .12       0
#XS Ineff= 2 , 0
          343.13 2005.97
Permanent Ineff=
       F       F
Bank Sta=359.9,376.3
XS Rating Curve= 0 ,0
Exp/Cntr=0.3,0.1

Type RM Length L Ch R = 1 ,20640.3 ,41.4,38.2,37.9
XS GIS Cut Line= 4
     2085130.036        174817.2     2085377.258      175075.533
     2085363.369      175106.089     2085607.813      175372.755
#Sta/Elev= 30
       0 2239.36      59 2195.57    75.4 2182.53   108.2 2159.77   114.8 2153.43
   124.7 2147.68   173.9 2113.45   206.7 2088.98   275.6 2039.52     292 2030.02
   301.8 2022.55   337.9 1999.24   341.2  1997.7  347.461997.904   375.9 1997.27
     385 1995.96   394.4 1993.58   400.9 1995.96  413.492001.824     427    2012
   456.3 2030.84   469.4 2037.52   482.4  2046.1     603 2113.28   664.9  2150.4
   681.2 2161.97     691 2164.31   700.7 2171.95   733.3  2189.2   752.9 2195.71
#Mann= 5 ,-1 , 0
       0     .12       0  347.46    .016       0     385    .045       0
   400.9    .016       0  413.49     .12       0
#XS Ineff= 2 , 0
          357.13 2001.53
Permanent Ineff=
       F       F
Bank Sta=385,400.9
XS Rating Curve= 0 ,0
Exp/Cntr=0.3,0.1

Type RM Length L Ch R = 1 ,20602.1 ,295.3,268.7,268.8
XS GIS Cut Line= 4
     2085102.952      174834.561     2085341.147      175083.867
     2085327.258      175114.422     2085582.119      175391.505
#Sta/Elev= 30
       0 2246.09    19.5 2231.75    48.8 2207.69    65.1  2196.6   120.4 2154.76
   175.6 2115.77   201.7 2094.39   234.2 2072.82     283 2036.47   328.5 2006.77
   344.8  1997.6   360.1 1994.51   369.2 1995.04   378.4 1992.82  384.051995.103
   388.2 1996.01   404.6 1995.96   407.8 1997.09  422.682006.314   473.3 2036.27
   538.8  2071.8   587.9 2100.01   653.4 2135.65   679.5 2152.07   689.4 2154.81
   699.2 2161.58   712.3  2169.1   731.9  2178.7   748.3 2184.72   754.8 2185.89
#Mann= 4 ,-1 , 0
       0     .12       0   369.2    .045       0  384.05    .016       0
  422.68     .12       0
Bank Sta=369.2,384.05
XS Rating Curve= 0 ,0
Exp/Cntr=0.3,0.1

Type RM Length L Ch R = 1 ,20333.4 ,258.8,263.2,267
XS GIS Cut Line= 2
     2084908.477      175005.993     2085403.269      175581.514
#Sta/Elev= 30
       0 2182.95    42.5 2159.16     121 2111.19   134.1 2102.07     157 2088.84
   186.5 2073.26   212.6 2057.85   255.2 2035.89   271.5 2028.87   323.9 1990.15
     337 1985.34     422 1987.27   428.6 1985.63   435.1  1986.7   441.6 1989.45
   464.6 1989.72   467.8 1990.98  475.271996.824     494 2008.28   500.5 2010.98
   510.4  2013.1   520.2 2017.22     579 2045.75     602 2054.07   628.1 2058.96
   667.4    2061     687 2056.52   700.1 2051.38   716.4 2049.25     759 2034.86
#Mann= 4 ,-1 , 0
       0     .12       0     422    .045       0   435.1    .016       0
  475.27     .12       0
Bank Sta=422,435.1
XS Rating Curve= 0 ,0
Exp/Cntr=0.3,0.1

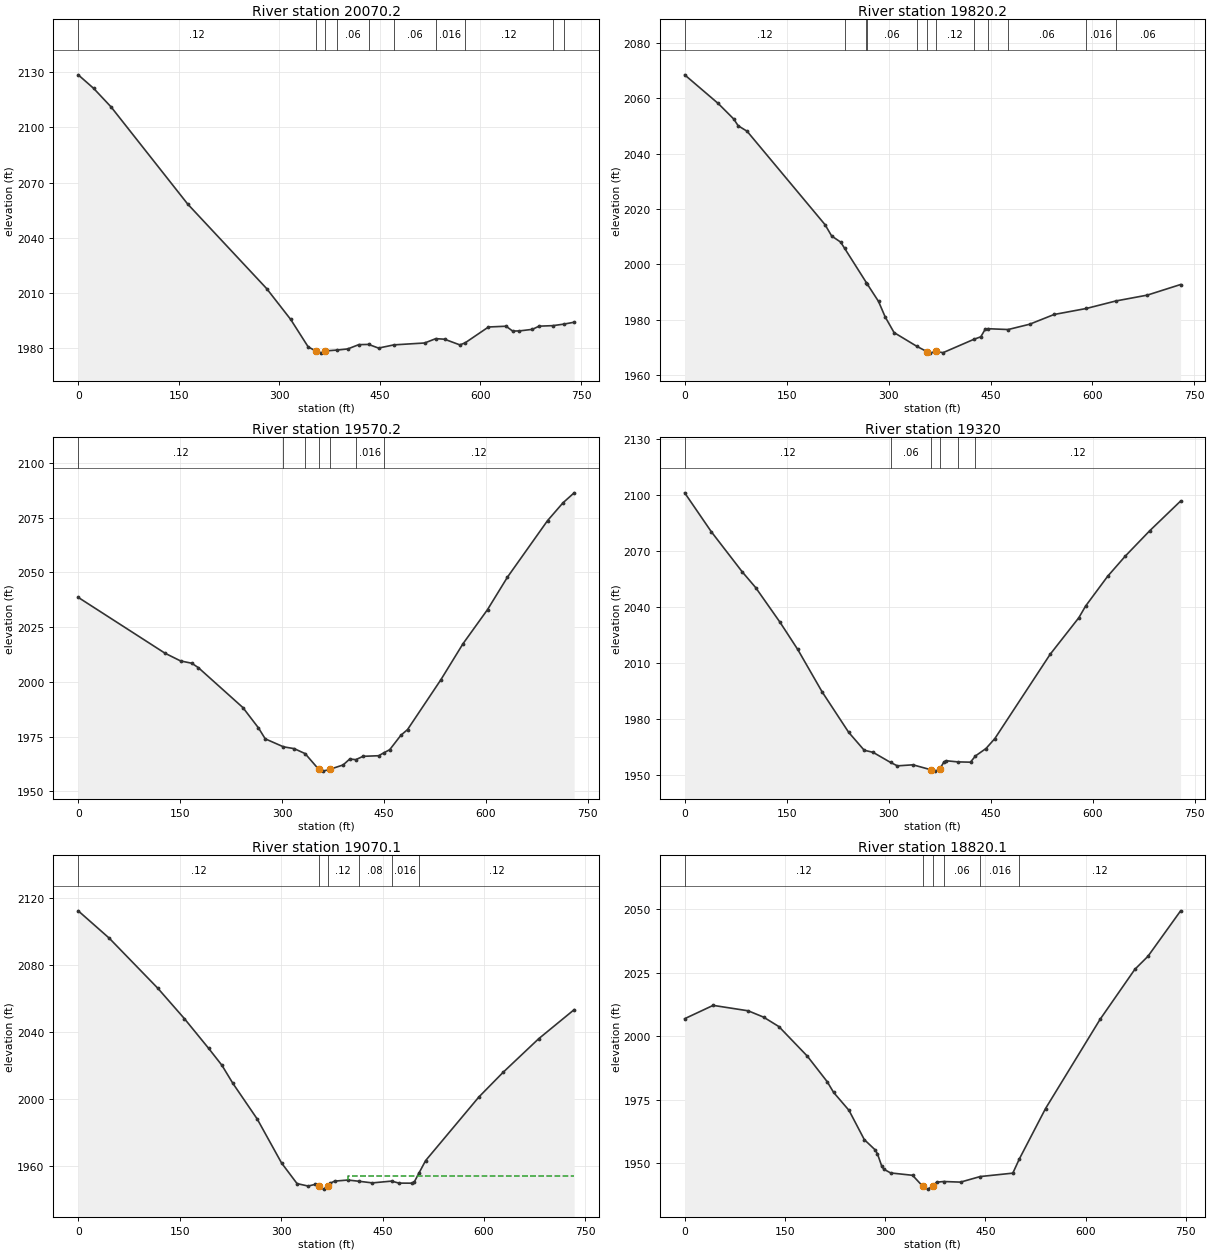
Type RM Length L Ch R = 1 ,20070.2 ,252.7,250,241.4
XS GIS Cut Line= 3
     2084781.675      175088.415     2084992.161      175383.825
     2085167.753      175717.558
#Sta/Elev= 30
       0 2128.58    22.9 2121.26      49 2111.15   163.4 2058.32     281 2012.46
     317 1995.63   343.1 1980.72  354.091978.584   362.7 1977.35  367.67  1978.5
  386.781979.044   402.1 1979.63   418.5 1981.96  433.211982.078     448 1980.09
  470.941981.839   516.8 1982.86  533.351985.215   546.4 1984.92   569.3 1981.83
  577.061982.912     612 1991.55   638.2 1991.97     648 1989.36   657.9 1989.41
   677.5 1990.27   687.4    1992  708.121992.284  723.961993.091   739.8 1994.14
#Mann= 10 ,-1 , 0
       0     .12       0  354.09    .045       0  367.67     .12       0
  386.78     .06       0  433.21     .12       0  470.94     .06       0
  533.35    .016       0  577.06     .12       0  708.12     .06       0
  723.96     .12       0
Bank Sta=354.09,367.67
XS Rating Curve= 0 ,0
Exp/Cntr=0.3,0.1

Type RM Length L Ch R = 1 ,19820.2 ,244,250,255.9
XS GIS Cut Line= 3
     2084530.573      175304.492     2084810.743      175536.569
      2085072.37      175792.324
#Sta/Elev= 30
       0 2068.49    49.2 2058.17    72.1 2052.56    78.7  2050.1    91.8 2048.12
   206.5 2014.38   216.3 2010.28   229.4  2008.1  235.192005.891   267.31993.452
  268.531992.975   285.2 1986.67     295 1981.07   308.1 1975.41   341.81970.415
   356.3 1968.55   360.5 1967.99   370.3 1968.62   380.1 1968.15  425.381972.965
   435.7 1973.89   442.2 1976.62   445.81976.811  475.911976.511   507.5 1978.42
   543.5 1981.94  590.971984.114  634.52 1986.83   680.7 1988.94   729.7 1992.77
#Mann= 12 ,-1 , 0
       0     .12       0  235.19     .06       0   267.3     .12       0
  268.53     .06       0   341.8     .12       0   356.3    .045       0
   370.3     .12       0  425.38     .06       0   445.8    .016       0
  475.91     .06       0  590.97    .016       0  634.52     .06       0
Bank Sta=356.3,370.3
XS Rating Curve= 0 ,0
Exp/Cntr=0.3,0.1

Type RM Length L Ch R = 1 ,19570.2 ,253.5,250.2,244.8
XS GIS Cut Line= 3
     2084414.753      175400.388     2084624.444      175697.452
     2084808.716      176013.878
#Sta/Elev= 30
       0 2038.63   127.8 2013.12   150.7  2009.6   167.1 2008.56   176.9 2006.52
   242.4  1988.3   265.3 1979.01   275.2 1974.05  302.011970.401   317.8 1969.57
  333.911967.297   353.8 1960.17   360.3  1959.3   370.2 1960.12   389.8 1962.12
   399.6 1964.84  408.48 1964.54   419.2 1966.06   442.1 1966.33  450.441967.782
   458.4 1969.09   474.8 1975.67   484.6 1978.27   533.6    2001   566.3  2017.5
   602.3 2033.04   631.7 2047.89   690.6 2073.65   713.4 2081.82   729.8 2086.36
#Mann= 7 ,-1 , 0
       0     .12       0  302.01     .06       0  333.91     .12       0
   353.8    .045       0   370.2     .12       0  408.48    .016       0
  450.44     .12       0
Bank Sta=353.8,370.2
XS Rating Curve= 0 ,0
Exp/Cntr=0.3,0.1

Type RM Length L Ch R = 1 ,19320   ,252.2,249.8,247
XS GIS Cut Line= 3
      2084183.19      175602.345      2084438.84       175862.77
     2084688.441      176127.968
#Sta/Elev= 30
       0 2101.05    39.1 2080.25    84.7 2058.71   104.3 2050.35   140.1 2031.79
   166.2  2017.2     202 1994.53   241.1 1972.83   263.9 1963.25     277 1962.12
  302.661956.707   312.8 1954.88   335.6 1955.44   361.7 1952.82   368.2 1952.06
   374.7 1953.04   381.2 1956.99   384.4 1957.62   401.31957.016   420.2 1956.85
  427.411960.174     443 1964.17     456  1969.5   537.3 2014.61   579.5 2034.21
   589.3 2040.37   621.8 2056.36   647.8 2067.19   683.6 2080.72   729.1 2096.66
#Mann= 6 ,-1 , 0
       0     .12       0  302.66     .06       0   361.7    .045       0
   374.7     .06       0   401.3    .016       0  427.41     .12       0
Bank Sta=361.7,374.7
XS Rating Curve= 0 ,0
Exp/Cntr=0.3,0.1

Type RM Length L Ch R = 1 ,19070.1 ,262.1,250,239.2
XS GIS Cut Line= 3
     2083964.922      175790.309     2084245.962      176019.824
     2084529.975      176257.765
#Sta/Elev= 30
       0  2112.5    45.8 2096.22   117.7 2066.33   156.9 2048.25   192.9 2030.45
   212.5 2020.37   228.8 2009.53   264.8 1988.26   300.7 1962.08   323.6  1949.8
     340 1948.32   349.8 1949.27   355.4 1948.23   362.8 1946.49   369.4 1948.34
   372.7 1950.03   379.2 1951.27   398.9 1951.91   414.8  1951.2     435 1950.21
   463.41951.277   474.3 1950.08     494 1950.04   497.3    1951  503.761955.966
   513.7 1963.48   592.4 2001.41   628.4 2016.19   680.9 2036.19   733.4 2053.54
#Mann= 6 ,-1 , 0
       0     .12       0   355.4    .045       0   369.4     .12       0
   414.8     .08       0   463.4    .016       0  503.76     .12       0
#XS Ineff= 2 , 0
                          398.88         1954.03
Permanent Ineff=
       F       F
Bank Sta=355.4,369.4
XS Rating Curve= 0 ,0
Exp/Cntr=0.3,0.1

Type RM Length L Ch R = 1 ,18820.1 ,119.5,121.3,120.2
XS GIS Cut Line= 3
     2083768.646      176178.403     2084128.882      176229.917
     2084496.051      176320.569
#Sta/Elev= 30
       0 2006.92    42.6 2012.16    95.1 2010.02     118 2007.54     141 2003.81
   183.6 1992.16   213.1 1982.19   222.9  1977.9   245.9 1970.84   268.8 1959.34
   285.2 1955.26   288.5  1953.7     295 1948.82   298.3 1947.65   308.2 1946.23
     341  1945.3   356.4 1940.93   363.9 1939.86   371.4 1941.14   376.9 1942.58
  387.481942.855   412.8 1942.62  442.171944.808     491 1946.15  500.851951.777
     540 1971.58   621.5 2006.63   673.6 2026.34   693.2 2031.46   742.1 2049.36
#Mann= 6 ,-1 , 0
       0     .12       0   356.4    .045       0   371.4     .12       0
  387.48     .06       0  442.17    .016       0  500.85     .12       0
Bank Sta=356.4,371.4
XS Rating Curve= 0 ,0
Exp/Cntr=0.3,0.1

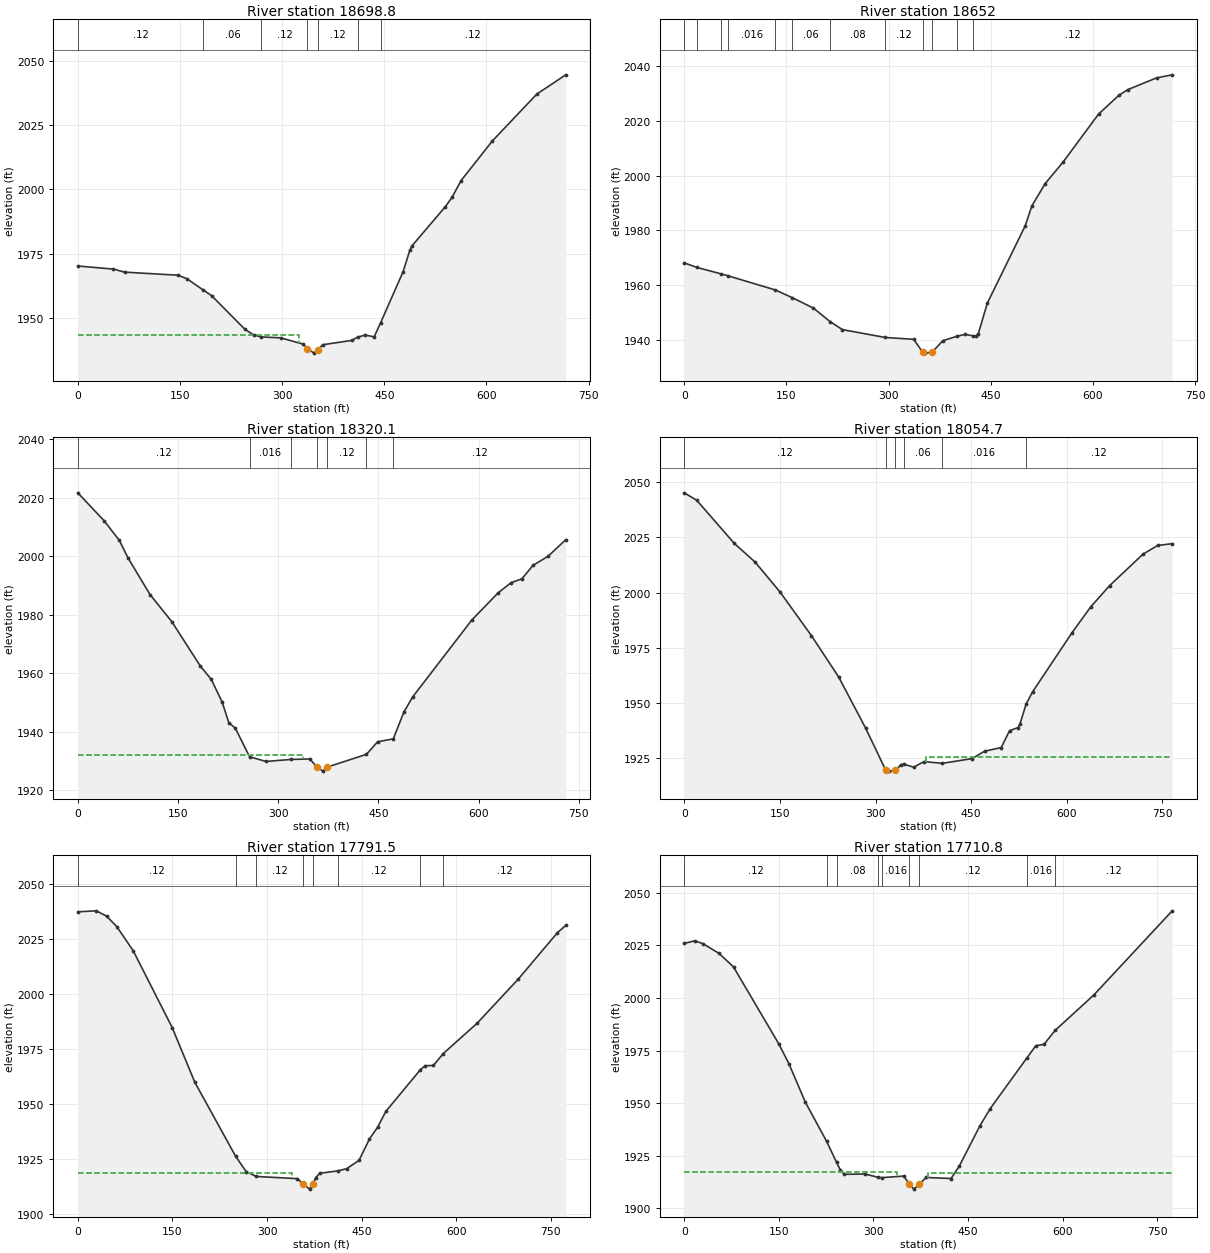
Type RM Length L Ch R = 1 ,18698.8 ,46.2,46.9,58.8
XS GIS Cut Line= 2
     2083763.369      176276.922     2084464.758      176422.755
#Sta/Elev= 30
       0 1970.13    52.3 1968.94    68.7 1967.75   147.2 1966.55   160.3 1965.17
  184.241960.777   196.3 1958.63   245.3 1945.52   258.4 1943.26  269.671942.532
   297.7 1942.18   330.4 1939.78   337.2 1938.01   346.8 1936.23   352.2 1937.51
   359.8  1939.5   402.4 1941.19  410.671942.433     422 1943.27   435.1 1942.56
  444.511948.007   477.6 1967.92   487.4 1976.24   490.7    1978   539.8 1993.28
   549.6 1996.93   562.6 2003.33   608.4 2018.73   673.9 2037.04   716.4 2044.54
#Mann= 7 ,-1 , 0
       0     .12       0  184.24     .06       0  269.67     .12       0
   337.2    .045       0   352.2     .12       0  410.67    .016       0
  444.51     .12       0
#XS Ineff= 2 , 0
          325.21 1943.12
Permanent Ineff=
       F       F
Bank Sta=337.2,352.2
XS Rating Curve= 0 ,0
Exp/Cntr=0.3,0.1

Type RM Length L Ch R = 1 ,18652   ,343.1,331.8,306.5
XS GIS Cut Line= 2
     2083758.508      176321.367     2084459.897        176467.2
#Sta/Elev= 30
       0  1968.1   19.051966.428   53.65 1964.12   63.691963.436  133.741958.209
  158.441955.405   189.7 1951.57  214.541946.549   232.2 1943.72  294.941940.842
   336.9 1940.17     350 1935.44   353.3 1935.12  363.981935.484   379.5 1939.65
  400.471941.286   412.2 1941.99  424.54  1941.4   428.5 1941.27   431.8 1942.29
   444.9 1953.37   500.5 1981.63   510.3 1988.95   529.9 1997.12   556.1 2004.95
   608.4 2022.56   637.9 2029.34     651 2031.44   693.5 2035.76   716.4 2036.87
#Mann= 12 ,-1 , 0
       0     .06       0   19.05    .016       0   53.65     .12       0
   63.69    .016       0  133.74     .12       0  158.44     .06       0
  214.54     .08       0  294.94     .12       0     350    .045       0
  363.98     .12       0  400.47    .016       0  424.54     .12       0
Bank Sta=350,363.98
XS Rating Curve= 0 ,0
Exp/Cntr=0.3,0.1

Type RM Length L Ch R = 1 ,18320.1 ,261.8,265.5,269.4
XS GIS Cut Line= 3
     2083841.983      176815.015     2084188.032      176703.785
     2084530.961      176573.299
#Sta/Elev= 30
       0 2021.66    39.3 2012.13    62.2 2005.39    75.3 1999.35   108.1 1986.89
   140.8 1977.59   183.4 1962.44   199.8 1957.89   216.1 1950.11     226  1943.1
   235.8 1941.21  257.031931.462   281.6 1929.83  319.35 1930.53   347.1 1930.69
  358.321927.924   366.8 1926.53   373.3  1927.9  432.131932.278   448.7 1936.55
  472.271937.573     488 1946.67   501.1 1951.85   589.5  1978.1   628.8  1987.4
   648.5 1990.93   664.9 1992.29   681.3 1996.86   704.2 2000.01   730.4 2005.65
#Mann= 7 ,-1 , 0
       0     .12       0  257.03    .016       0  319.35     .12       0
  358.32    .045       0   373.3     .12       0  432.13    .016       0
  472.27     .12       0
#XS Ineff= 2 , 0
          337.69 1932.17
Permanent Ineff=
       F       F
Bank Sta=358.32,373.3
XS Rating Curve= 0 ,0
Exp/Cntr=0.3,0.1

Type RM Length L Ch R = 1 ,18054.7 ,268.1,263.2,256.6
XS GIS Cut Line= 2
     2083898.061      177004.691     2084653.269      176880.993
#Sta/Elev= 30
       0 2045.13    19.6 2041.74    78.5 2022.24   111.2 2013.78   150.4  2000.2
   199.5  1980.5     242  1961.9   284.5 1938.69   315.8 1919.76   320.5 1919.26
   330.8 1919.59   340.1 1922.25  345.081922.337   359.7 1921.05   376.1 1923.57
  404.681922.787   451.3 1924.92   470.9 1928.25   497.1 1929.94   510.2 1937.56
   523.3 1938.93   526.5 1940.59  536.121949.527   546.2 1955.09   608.3 1981.93
   637.7 1993.64   667.2 2003.18   719.5  2017.4   742.4 2021.32   765.3 2022.14
#Mann= 6 ,-1 , 0
       0     .12       0   315.8    .045       0   330.8     .12       0
  345.08     .06       0  404.68    .016       0  536.12     .12       0
#XS Ineff= 2 , 0
                          379.59         1925.43
Permanent Ineff=
       F       F
Bank Sta=315.8,330.8
XS Rating Curve= 0 ,0
Exp/Cntr=0.3,0.1

Type RM Length L Ch R = 1 ,17791.5 ,79.4,80.7,79.5
XS GIS Cut Line= 4
     2083932.609      177223.354     2084280.036      177200.533
     2084307.119      177183.172     2084699.167      177150.836
#Sta/Elev= 30
       0 2037.32    29.3 2037.77    45.6 2035.35    61.8 2030.59    87.9 2019.61
   149.7 1984.69   185.5 1959.88  250.171926.256   266.8  1919.3  282.821917.048
   348.2 1916.05  357.111913.713   367.5 1911.29  372.831913.617   377.1 1916.44
   383.6 1918.49  412.111919.568   426.2 1920.57   445.9 1924.36   462.3 1933.99
   475.4 1939.43   488.5 1946.65  543.25 1965.58   550.8 1967.38   563.9 1967.49
  579.25 1972.85   632.8 1986.57   698.3  2006.7   760.6 2027.87   773.7 2031.13
#Mann= 8 ,-1 , 0
       0     .12       0  250.17     .06       0  282.82     .12       0
  357.11    .045       0  372.83    .016       0  412.11     .12       0
  543.25    .016       0  579.25     .12       0
#XS Ineff= 2 , 0
          339.68 1918.73
Permanent Ineff=
       F       F
Bank Sta=357.11,372.83
XS Rating Curve= 0 ,0
Exp/Cntr=0.3,0.1

Type RM Length L Ch R = 1 ,17710.8 ,132.3,140.6,150.4
XS GIS Cut Line= 4
      2083949.97      177301.132     2084297.397      177278.311
      2084324.48       177260.95     2084716.529      177228.614
#Sta/Elev= 30
       0 2025.93    16.3 2027.14    29.3 2025.87    55.3 2021.16    78.1 2014.74
   149.7 1978.28     166  1968.7     192 1950.46  225.781931.837  241.411921.911
   247.3 1918.36   253.8 1916.19   286.4 1916.35  307.731914.743  313.841914.625
   348.2 1915.38  356.811911.479   364.3 1909.16  372.34 1911.52   383.6  1914.7
     423 1914.21   436.1 1920.12   468.9 1939.33   485.2 1947.46  543.281971.517
   557.4 1977.31   570.5 1978.01     5881984.587   649.2 2001.37   773.7 2041.42
#Mann= 9 ,-1 , 0
       0     .12       0  225.78     .06       0  241.41     .08       0
  307.73     .06       0  313.84    .016       0  356.81    .045       0
  372.34     .12       0  543.28    .016       0     588     .12       0
#XS Ineff= 2 , 0
          337.91 1917.15  387.17          1916.9
Permanent Ineff=
       F       F
Bank Sta=356.81,372.34
XS Rating Curve= 0 ,0
Exp/Cntr=0.3,0.1