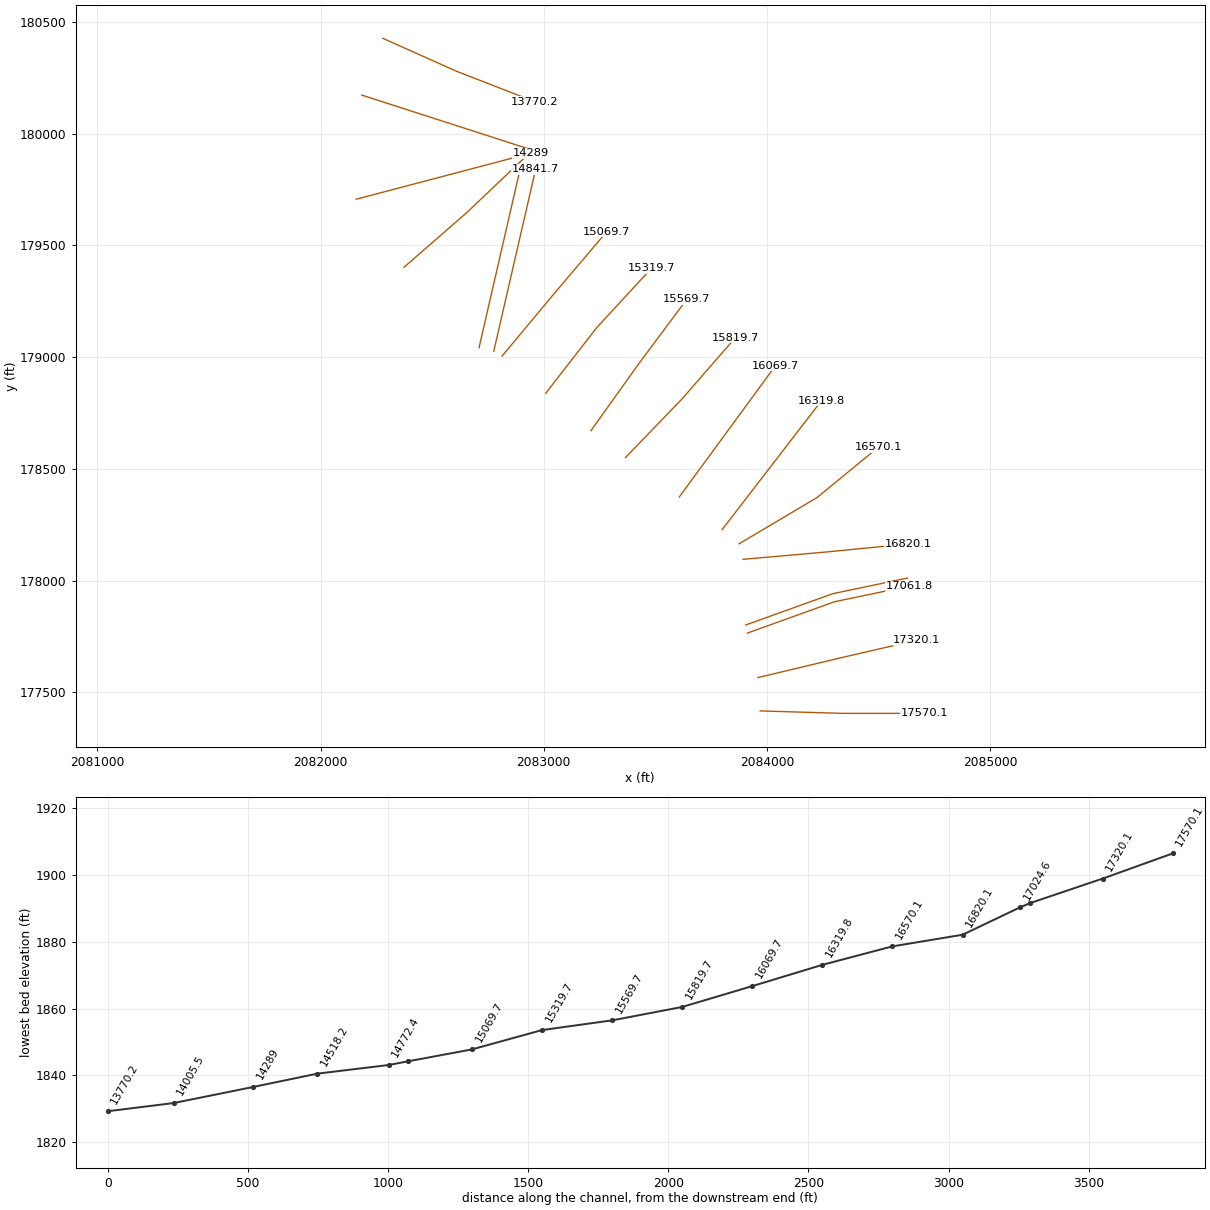
HEC-RAS study RCKCMPCK.prj: RCKCMPCK

--- RCKCMPCK.g01 (geometry) --- (continued)

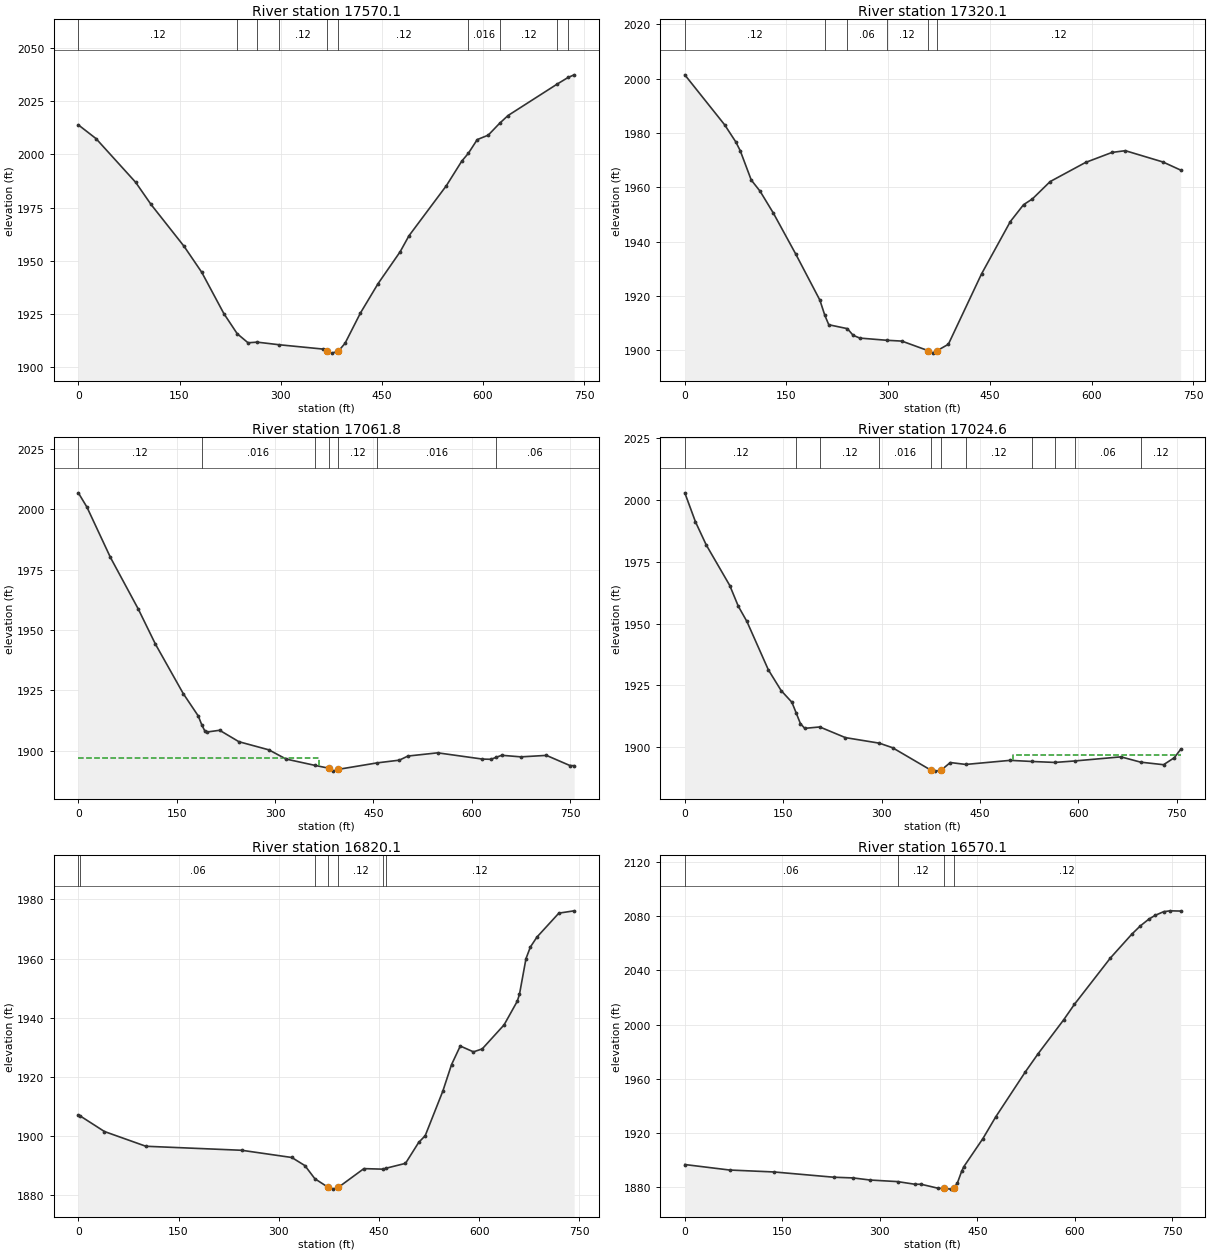
Type RM Length L Ch R = 1 ,17570.1 ,243.8,250,255
XS GIS Cut Line= 3
     2083969.352      177416.765     2084341.758      177405.801
     2084704.246      177405.801
#Sta/Elev= 30
       0 2013.91    26.2 2007.46      85 1986.86   107.8 1976.43   156.9 1956.67
     183 1944.48   215.7 1925.08  235.541915.572   251.6  1911.3   265.11911.606
  297.841910.373   362.8 1908.34   369.3 1907.31   375.8 1906.43   385.6 1907.39
   395.4 1911.05   418.3 1925.36   444.4 1939.17   477.1 1954.16   490.1 1961.65
   545.6 1985.26   568.5 1996.85  578.272000.539   591.4 2006.98   607.7 2009.07
   624.7 2014.69   637.1 2018.32  710.072033.153  726.022036.223   735.1 2037.48
#Mann= 10 ,-1 , 0
       0     .12       0  235.54     .08       0   265.1    .016       0
  297.84     .12       0   369.3    .045       0   385.6     .12       0
  578.27    .016       0   624.7     .12       0  710.07     .08       0
  726.02     .12       0
Bank Sta=369.3,385.6
XS Rating Curve= 0 ,0
Exp/Cntr=0.3,0.1

Type RM Length L Ch R = 1 ,17320.1 ,255,258.4,260.1
XS GIS Cut Line= 3
     2083959.057       177565.87     2084314.981      177650.967
     2084671.009      177733.333
#Sta/Elev= 30
       0 2001.37    58.8 1982.96    75.2 1976.68    81.7 1973.48      98 1962.65
   111.1  1958.5   130.7 1950.43   163.4  1935.5   199.3 1918.39  206.591912.798
   212.4 1909.35  239.821907.914   248.3 1905.47   258.1 1904.44  297.95 1903.63
   320.2 1903.33   358.5 1899.85     366  1898.9   372.5 1899.84   388.8 1902.17
   437.7 1928.06   480.2 1947.34   499.7 1953.55   512.8 1955.69   538.9 1962.06
   591.1  1969.1   630.2  1972.8   649.8 1973.44   705.3 1969.28   731.4  1966.3
#Mann= 6 ,-1 , 0
       0     .12       0  206.59    .016       0  239.82     .06       0
  297.95     .12       0   358.5    .045       0   372.5     .12       0
Bank Sta=358.5,372.5
XS Rating Curve= 0 ,0
Exp/Cntr=0.3,0.1

Type RM Length L Ch R = 1 ,17061.8 ,37.2,37.1,37.2
XS GIS Cut Line= 3
      2083911.98      177765.117     2084302.258      177905.394
     2084636.444      177975.172
#Sta/Elev= 30
       0 2006.85    13.1 2000.94      49 1980.07    91.4 1958.72   117.6 1944.17
     160 1923.69   182.9 1914.42  188.331910.692   192.7 1908.33   195.9 1907.77
   215.5  1908.5   244.9 1903.76   290.6 1900.39   316.8 1896.58  360.181894.001
   381.5 1892.81   388.6 1891.58   396.5 1892.32  455.971895.008   489.5 1896.12
   502.5 1897.82     548 1899.16   616.3 1896.57   629.3 1896.48   637.41897.323
   645.6 1898.14   674.8 1897.49   713.8  1898.1   749.6  1893.9   756.1 1893.83
#Mann= 7 ,-1 , 0
       0     .12       0  188.33    .016       0  360.18     .12       0
   381.5    .045       0   396.5     .12       0  455.97    .016       0
   637.4     .06       0
#XS Ineff= 2 , 0
          366.42 1896.82
Permanent Ineff=
       F       F
Bank Sta=381.5,396.5
XS Rating Curve= 0 ,0
Exp/Cntr=0.3,0.1

Type RM Length L Ch R = 1 ,17024.6 ,209.8,204.5,198
XS GIS Cut Line= 3
     2083904.341      177801.228     2084294.619      177941.505
     2084628.805      178011.283
#Sta/Elev= 30
       0 2002.94    16.3 1991.18    32.7 1981.84    68.6 1965.41    81.6 1957.02
    94.7 1950.86   127.4 1931.28     147 1922.85   163.3 1918.15  170.121913.643
   176.3 1909.51   182.9 1907.58  205.821908.145   244.9 1903.83  296.571901.583
   316.8 1899.74   375.5 1890.62   382.1 1890.26  390.67 1890.61   404.9 1893.74
  428.491892.968     496 1894.62  530.041894.161  564.33 1893.78  594.511894.376
   665.1 1896.04   695.2 1893.89   730.1 1892.86   746.4 1895.68   756.1 1899.07
#Mann= 11 ,-1 , 0
       0     .12       0  170.12    .016       0  205.82     .12       0
  296.57    .016       0   375.5    .045       0  390.67    .016       0
  428.49     .12       0  530.04     .06       0  564.33     .12       0
  594.51     .06       0   695.2     .12       0
#XS Ineff= 2 , 0
                          499.94         1896.86
Permanent Ineff=
       F       F
Bank Sta=375.5,390.67
XS Rating Curve= 0 ,0
Exp/Cntr=0.3,0.1

Type RM Length L Ch R = 1 ,16820.1 ,239.8,250,263.2
XS GIS Cut Line= 3
     2083892.233      178095.168     2084272.358      178128.638
     2084631.361      178163.996
#Sta/Elev= 30
       0 1907.02    2.131906.917    39.1 1901.56   101.1 1896.58   244.6 1895.22
   319.6 1892.78   339.2 1890.04  354.141885.596   374.1 1882.69   381.6 1882.09
   389.1 1882.66   427.5 1889.02   456.21888.836  460.791889.162   489.8  1890.8
   509.5 1897.86   519.3 1900.15   545.6 1915.16   558.7 1924.16   571.8 1930.46
   591.5 1928.49   604.6 1929.47   637.4 1937.61   657.1 1945.58   660.4 1947.91
   670.2 1960.01   676.8 1963.94   686.6 1967.28   719.4 1975.37   742.3 1976.15
#Mann= 7 ,-1 , 0
       0    .016       0    2.13     .06       0  354.14     .12       0
   374.1    .045       0   389.1     .12       0   456.2     .06       0
  460.79     .12       0
Bank Sta=374.1,389.1
XS Rating Curve= 0 ,0
Exp/Cntr=0.3,0.1

Type RM Length L Ch R = 1 ,16570.1 ,241.6,250.3,255.4
XS GIS Cut Line= 3
     2083874.358      178164.498     2084223.738      178371.471
     2084499.277        178597.6
#Sta/Elev= 30
       0 1896.77    68.8 1892.72   137.5 1891.28   229.2  1887.4   258.7 1886.89
   284.9 1885.34  327.371884.163   353.7 1882.23   363.5 1882.21   389.7 1879.25
   398.6 1879.09   409.4 1878.62   413.6 1879.42   419.2 1883.16   425.7 1891.69
     429 1895.13   458.4  1915.9     478 1931.82   523.8 1965.22   543.4 1978.59
   582.7  2003.6     599 2014.89   654.6 2049.25   687.3  2066.7   700.4 2072.83
   713.5 2077.82   723.3 2080.67   736.4 2083.37   746.2    2084   762.5 2083.83
#Mann= 4 ,-1 , 0
       0     .06       0  327.37     .12       0   398.6    .045       0
   413.6     .12       0
Bank Sta=398.6,413.6
XS Rating Curve= 0 ,0
Exp/Cntr=0.3,0.1

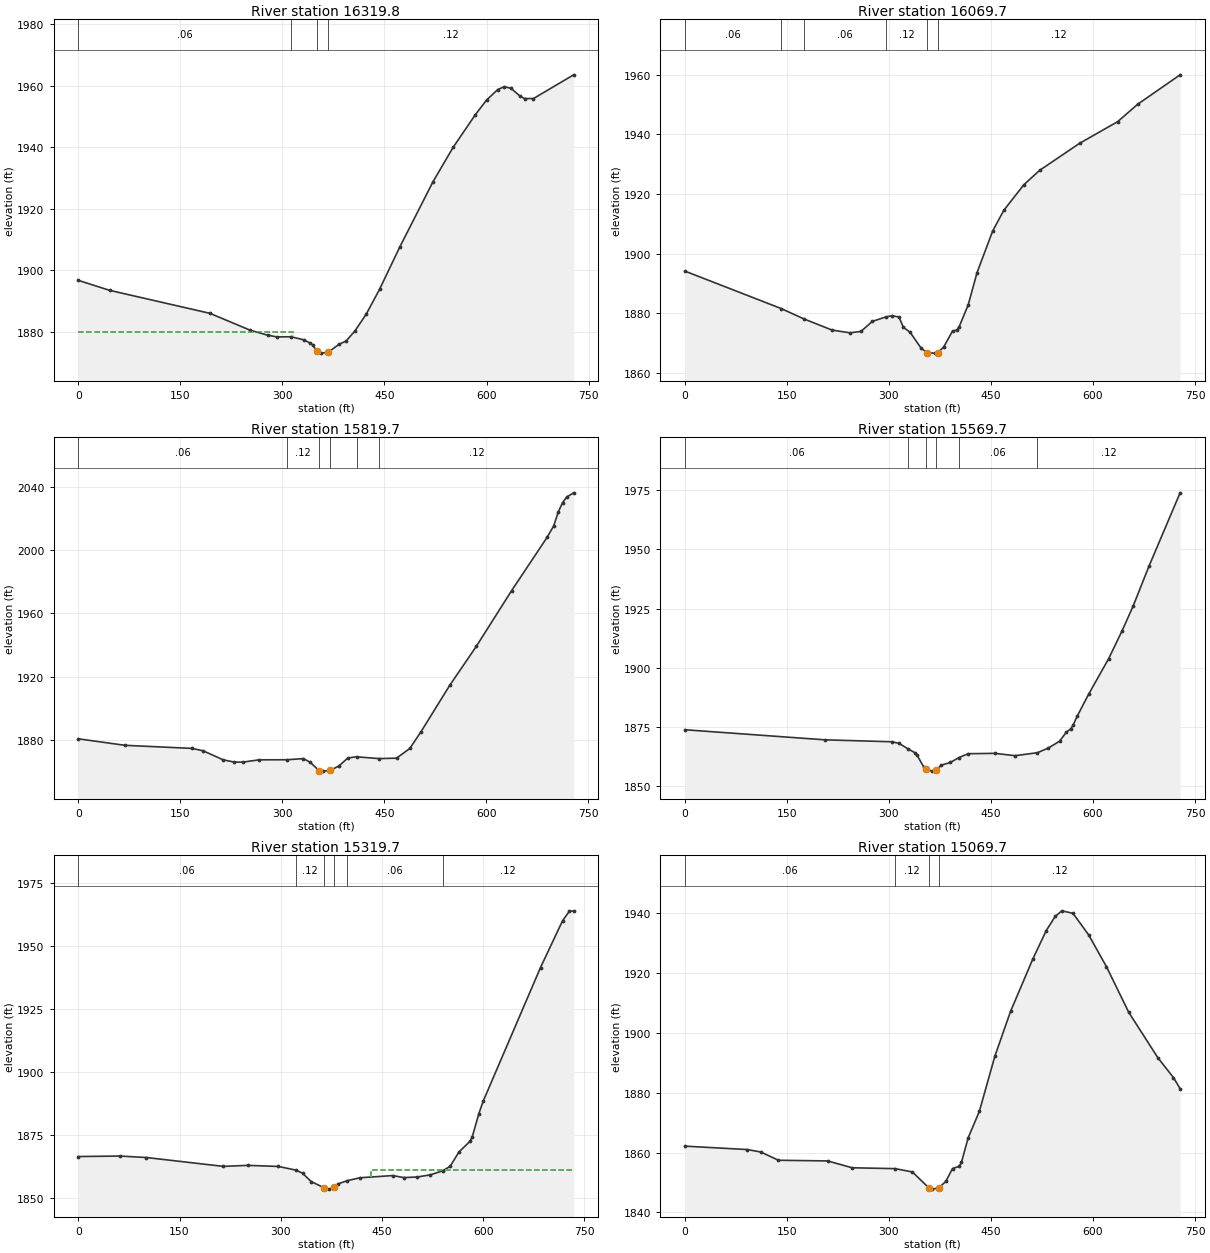
Type RM Length L Ch R = 1 ,16319.8 ,249.5,250.1,250.6
XS GIS Cut Line= 3
     2083798.778      178228.086     2084021.067      178516.329
     2084243.355      178804.572
#Sta/Elev= 30
       0 1896.75    45.9 1893.51   193.5 1886.02   252.5 1880.54   278.7 1878.89
   291.9 1878.36   312.61878.407   331.2 1877.42     341 1876.33   344.3  1875.8
   350.9 1873.65   357.4 1873.08   367.3 1873.38   383.7 1876.02   393.5    1877
   406.6  1880.3     423 1885.69   442.7 1893.81   472.2 1907.48   521.4 1928.87
   550.9 1940.02   583.7 1950.68   600.1  1955.4   616.5 1958.82   626.3 1959.76
   636.2 1959.17   649.3 1956.65   655.9 1955.88     669 1955.89     728  1963.6
#Mann= 4 ,-1 , 0
       0     .06       0   312.6     .12       0   350.9    .045       0
   367.3     .12       0
#XS Ineff= 2 , 0
          315.77 1880.04
Permanent Ineff=
       F       F
Bank Sta=350.9,367.3
XS Rating Curve= 0 ,0
Exp/Cntr=0.3,0.1

Type RM Length L Ch R = 1 ,16069.7 ,253,250,248
XS GIS Cut Line= 3
     2083606.605       178373.82     2083821.861      178667.351
     2084037.117      178960.883
#Sta/Elev= 30
       0 1894.22   141.71881.653  175.181878.177   216.4 1874.45   242.7 1873.52
   259.1 1874.01   275.5 1877.34  295.691878.854     305 1879.27   314.8 1878.79
   321.4 1875.37   331.2  1873.7   347.6 1868.31   356.5 1866.82   367.3 1866.72
   371.5 1866.84   380.4 1868.72   393.5  1874.1   400.1 1874.48   403.4 1875.62
   416.5 1882.85   429.6 1893.72   452.5 1907.62   468.9 1914.58   498.4 1923.15
   521.4 1927.94   580.4 1937.04   636.2 1944.27   665.7 1950.12     728 1959.97
#Mann= 6 ,-1 , 0
       0     .06       0   141.7    .016       0  175.18     .06       0
  295.69     .12       0   356.5    .045       0   371.5     .12       0
Bank Sta=356.5,371.5
XS Rating Curve= 0 ,0
Exp/Cntr=0.3,0.1

Type RM Length L Ch R = 1 ,15819.7 ,246.5,250,251.6
XS GIS Cut Line= 3
     2083365.647      178550.449     2083618.432      178812.211
     2083858.079      179086.983
#Sta/Elev= 30
       0 1880.87    68.8 1876.77   167.2 1874.83   183.6 1873.31   213.1 1867.61
   229.5 1866.17   242.6 1866.19   265.6 1867.61  306.511867.663   331.1 1868.38
     341  1866.1   354.1 1860.82   360.6 1860.48   370.4 1860.92   383.4 1863.77
   396.4 1868.78  409.171869.529  442.421868.386   468.1 1868.67   487.6 1874.82
   503.9 1885.28   546.2 1914.58   585.3 1939.22   637.3 1974.44   689.4 2008.04
   699.2 2015.33   705.7 2023.85   712.2 2029.99   718.7 2033.65   728.5 2036.18
#Mann= 6 ,-1 , 0
       0     .06       0  306.51     .12       0   354.1    .045       0
   370.4     .12       0  409.17     .06       0  442.42     .12       0
Bank Sta=354.1,370.4
XS Rating Curve= 0 ,0
Exp/Cntr=0.3,0.1

Type RM Length L Ch R = 1 ,15569.7 ,250.8,250,247.6
XS GIS Cut Line= 3
     2083211.292      178670.914     2083423.081      178967.061
     2083640.557      179258.934
#Sta/Elev= 30
       0 1873.91   206.6 1869.65     305 1868.84   314.9 1868.16  328.181865.859
   337.8  1864.3   341.1 1863.35     351 1858.37   354.2 1857.31   364.1 1856.47
  369.421857.025   377.2 1858.99   390.3 1860.12  402.981862.183   416.6 1863.81
   455.9 1863.96   485.4 1862.98   518.3 1864.23   534.6 1866.22     551  1869.1
   560.8 1872.88   567.4 1874.31   570.7  1875.8   577.2 1879.81   593.6 1888.86
   623.1 1903.88   642.8 1915.59   659.2 1926.12   682.2 1942.74   728.1 1973.76
#Mann= 6 ,-1 , 0
       0     .06       0  328.18     .12       0   354.2    .045       0
  369.42     .12       0  402.98     .06       0   518.3     .12       0
Bank Sta=354.2,369.42
XS Rating Curve= 0 ,0
Exp/Cntr=0.3,0.1

Type RM Length L Ch R = 1 ,15319.7 ,250.3,250,250.2
XS GIS Cut Line= 3
     2083009.032      178838.561     2083236.956      179131.739
     2083482.971      179398.253
#Sta/Elev= 30
       0 1866.51    61.9 1866.71     101 1866.12     215  1862.6   250.8    1863
   296.4 1862.58  323.071861.089   332.3 1859.88   345.3 1856.54   363.9 1854.17
   371.4 1853.57   378.9 1854.27   384.4  1855.6  398.861856.946   417.1 1858.07
   466.1 1858.96   482.4 1858.15   502.1 1858.39   521.7 1859.24  539.881860.825
   551.1 1862.62   564.1 1868.33   580.5 1872.56   583.8 1874.29   593.6 1883.51
   600.1 1888.53     685 1941.56   717.7 1960.14   727.5 1963.83   734.1 1964.08
#Mann= 6 ,-1 , 0
       0     .06       0  323.07     .12       0   363.9    .045       0
   378.9     .12       0  398.86     .06       0  539.88     .12       0
#XS Ineff= 2 , 0
                          433.31         1861.15
Permanent Ineff=
       F       F
Bank Sta=363.9,378.9
XS Rating Curve= 0 ,0
Exp/Cntr=0.3,0.1

Type RM Length L Ch R = 1 ,15069.7 ,215.8,228,238.7
XS GIS Cut Line= 3
     2082813.506      179005.035     2083046.744      179284.521
     2083282.437      179561.906
#Sta/Elev= 30
       0 1862.14    91.8    1861   111.5 1860.19   137.7 1857.42   209.9  1857.2
     246 1854.91  308.981854.627   334.5 1853.52  358.871848.166     364 1847.78
   373.9 1848.29   383.7 1850.38   393.5 1854.65   403.4  1855.4   406.6 1856.68
   416.5  1864.9   432.9 1873.72   455.8  1892.2   478.8 1907.14   511.6 1924.67
   531.3 1934.15   544.4 1938.84   554.2 1940.73   570.6 1939.89   593.6 1932.69
   619.8 1922.07   652.6 1906.79   695.2 1891.71   718.2 1885.04     728 1881.36
#Mann= 4 ,-1 , 0
       0     .06       0  308.98     .12       0  358.87    .045       0
   373.9     .12       0
Bank Sta=358.87,373.9
XS Rating Curve= 0 ,0
Exp/Cntr=0.3,0.1

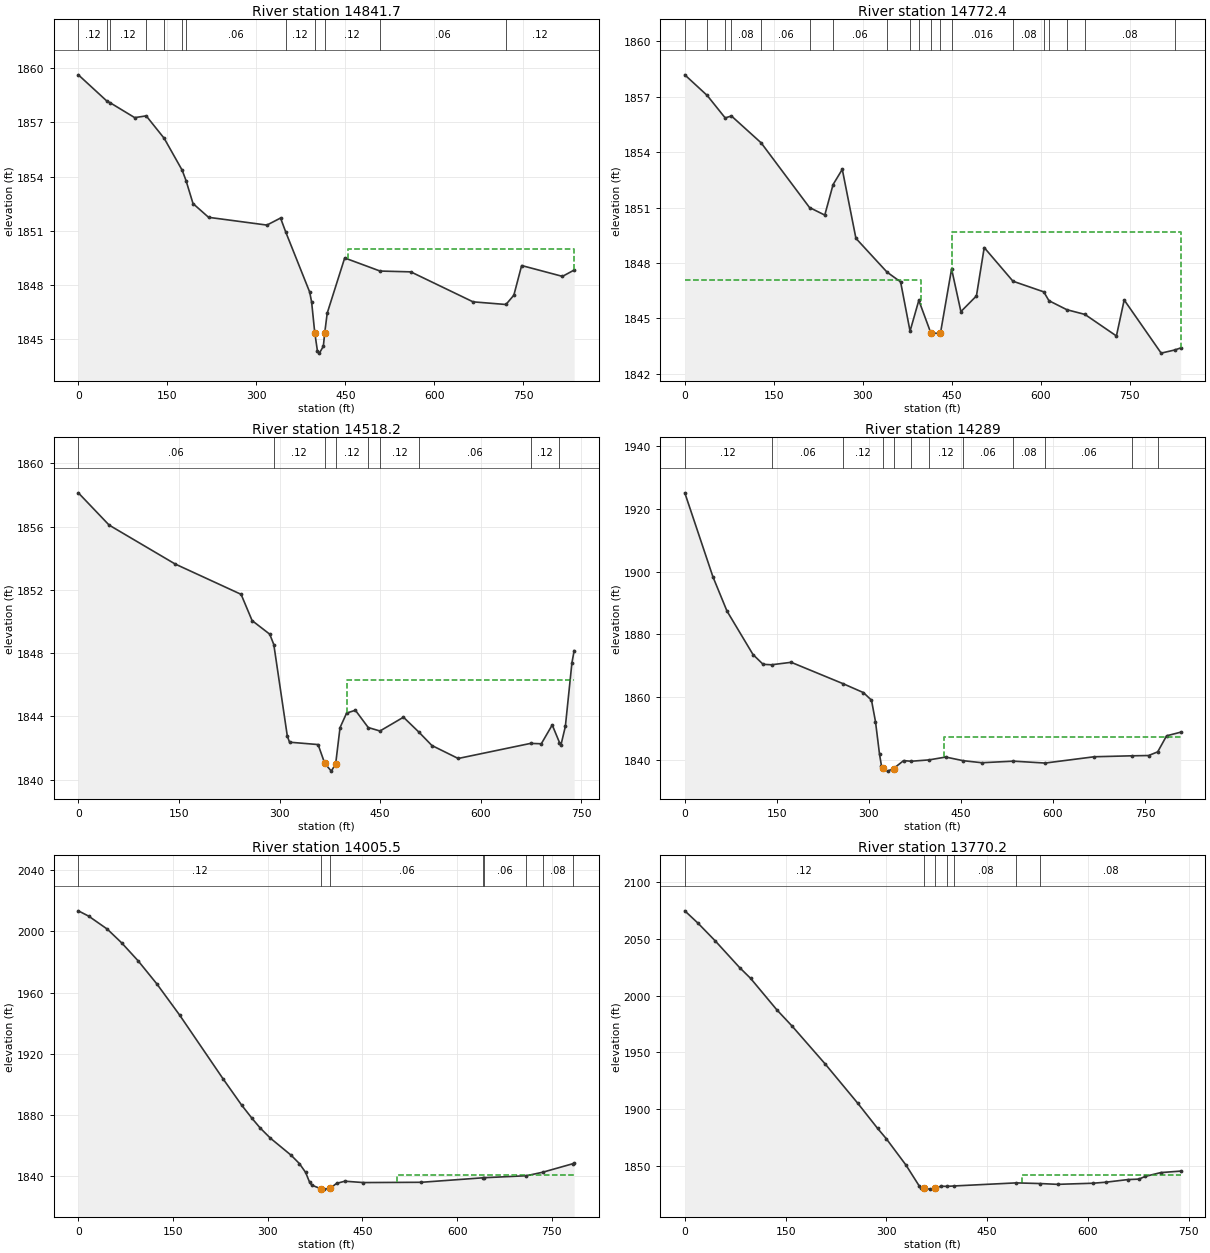
Type RM Length L Ch R = 1 ,14841.7 ,70.8,69.3,69.6
XS GIS Cut Line= 2
     2082776.077      179026.922     2082963.577      179841.158
#Sta/Elev= 30
       0 1859.63   47.871858.184   53.181858.092      95 1857.26  114.411857.357
  144.721856.112  175.031854.346  181.491853.775   193.3  1852.5   219.5 1851.74
   317.8 1851.31   340.8  1851.7  349.771850.906   389.9  1847.6   393.2 1847.04
  398.431845.353     403 1844.33   406.3 1844.22   412.9  1844.6  415.181845.324
   419.4 1846.43   448.9 1849.49  508.471848.765   560.3 1848.72   665.2 1847.06
  720.661846.913     734 1847.43   747.1 1849.07   815.9 1848.47   835.6 1848.82
#Mann= 12 ,-1 , 0
       0     .12       0   47.87     .06       0   53.18     .12       0
  114.41     .06       0  144.72     .08       0  175.03    .016       0
  181.49     .06       0  349.77     .12       0  398.43    .045       0
  415.18     .12       0  508.47     .06       0  720.66     .12       0
#XS Ineff= 2 , 0
                           454.8         1849.98
Permanent Ineff=
       F       F
Bank Sta=398.43,415.18
XS Rating Curve= 0 ,0
Exp/Cntr=0.3,0.1

Type RM Length L Ch R = 1 ,14772.4 ,267.4,254.2,240.1
XS GIS Cut Line= 2
     2082710.105      179042.547     2082897.605      179856.783
#Sta/Elev= 30
       0 1858.19   37.741857.072   68.061855.855   78.58 1855.96  128.681854.504
  210.18    1851   235.9 1850.59  249.931852.246   265.4 1853.07   288.4 1849.33
   340.8  1847.5   363.7 1846.97  379.61  1844.3  394.39 1845.97  414.721844.194
   430.81844.183  449.621847.672   465.3 1845.36   491.5 1846.21   504.6 1848.83
  553.061847.007  604.97 1846.43  613.681845.951  643.991845.461   674.31845.208
   727.4 1844.04   740.5 1845.99   802.8 1843.11  825.871843.282   835.6 1843.39
#Mann= 19 ,-1 , 0
       0    .016       0   37.74     .08       0   68.06     .06       0
   78.58     .08       0  128.68     .06       0  210.18     .08       0
  249.93     .06       0   340.8     .12       0  379.61     .06       0
  394.39     .12       0  414.72    .045       0   430.8     .12       0
  449.62    .016       0  553.06     .08       0  604.97    .016       0
  613.68     .08       0  643.99     .12       0   674.3     .08       0
  825.87     .12       0
#XS Ineff= 2 , 0
          397.32 1847.05  450.98         1849.69
Permanent Ineff=
       F       F
Bank Sta=414.72,430.8
XS Rating Curve= 0 ,0
Exp/Cntr=0.3,0.1

Type RM Length L Ch R = 1 ,14518.2 ,239.3,229.2,217.6
XS GIS Cut Line= 3
     2082373.873      179401.891     2082655.898      179647.445
     2082920.768      179899.038
#Sta/Elev= 30
       0 1858.13    45.9 1856.09   144.3 1853.63   242.7 1851.71   259.1 1850.05
   285.4 1849.19  291.471848.533   311.6 1842.75   314.9 1842.36   357.5 1842.21
   367.4 1841.02   377.2 1840.53   383.7 1840.99   390.2 1843.28     400  1844.2
   413.1 1844.38  432.241843.288  449.741843.068   484.8 1843.94  507.951842.991
   527.2 1842.15   566.4 1841.33  674.311842.284   690.3 1842.26   706.6 1843.45
  717.411842.339   719.7  1842.2   726.2 1843.36     736 1847.39   739.3 1848.15
#Mann= 9 ,-1 , 0
       0     .06       0  291.47     .12       0   367.4    .045       0
   383.7     .12       0  432.24    .016       0  449.74     .12       0
  507.95     .06       0  674.31     .12       0  717.41    .016       0
#XS Ineff= 2 , 0
                          400.41         1846.28
Permanent Ineff=
       F       F
Bank Sta=367.4,383.7
XS Rating Curve= 0 ,0
Exp/Cntr=0.3,0.1

Type RM Length L Ch R = 1 ,14289   ,296.5,283.5,270.4
XS GIS Cut Line= 2
      2082159.78      179706.514      2082941.03      179912.243
#Sta/Elev= 30
       0 1925.05    45.8 1898.36    68.7 1887.46   111.2  1873.6   127.6 1870.51
  141.281870.364   173.4 1871.15   258.5  1864.3   291.1 1861.51   304.2  1859.1
   310.7  1852.3   317.3 1841.89   320.5 1838.18  322.231837.472   330.4 1836.54
   340.2 1837.37   356.5 1839.88  368.94 1839.68  398.281840.121   425.2 1841.02
  453.421839.864   484.1 1839.21  535.361839.712   587.21839.109   667.2 1841.11
  728.641841.415   755.6  1841.5  770.541842.665     785 1847.77   807.9 1848.92
#Mann= 12 ,-1 , 0
       0     .12       0  141.28     .06       0   258.5     .12       0
  322.23    .045       0   340.2     .12       0  368.94     .06       0
  398.28     .12       0  453.42     .06       0  535.36     .08       0
   587.2     .06       0  728.64     .12       0  770.54    .016       0
#XS Ineff= 2 , 0
                          422.08         1847.36
Permanent Ineff=
       F       F
Bank Sta=322.23,340.2
XS Rating Curve= 0 ,0
Exp/Cntr=0.3,0.1

Type RM Length L Ch R = 1 ,14005.5 ,237.6,235.3,233.7
XS GIS Cut Line= 2
     2082184.519       180172.66     2082931.915      179931.775
#Sta/Elev= 30
       0 2013.47    16.4    2010    45.8 2001.54    68.7 1992.53    94.9 1980.73
   124.3 1965.78   160.3 1945.48     229  1903.9   258.5 1886.68   274.8 1878.11
   287.9  1871.7   304.3 1864.97     337 1853.87   350.1 1848.42   359.9  1842.7
   366.4 1836.13   369.7 1834.35   383.8 1832.01   389.4 1831.73   398.8 1832.25
     409 1835.48   422.1  1836.9   451.5 1836.02   543.1 1836.19  641.69 1839.16
  641.87 1839.16  709.771840.471  735.571842.775  784.221848.441   785.3 1848.51
#Mann= 8 ,-1 , 0
       0     .12       0   383.8    .045       0   398.8     .06       0
  641.69     .12       0  641.87     .06       0  709.77     .12       0
  735.57     .08       0  784.22    .016       0
#XS Ineff= 2 , 0
                          504.46         1841.17
Permanent Ineff=
       F       F
Bank Sta=383.8,398.8
XS Rating Curve= 0 ,0
Exp/Cntr=0.3,0.1

Type RM Length L Ch R = 1 ,13770.2 ,293.4,294.8,294.4
XS GIS Cut Line= 3
     2082279.416      180426.461     2082609.735      180278.907
     2082960.237      180142.827
#Sta/Elev= 30
       0 2074.74    19.6 2063.88    45.6 2048.04    81.5 2024.73    97.8 2015.25
   136.9 1987.46   159.7 1973.05   208.6 1939.88   257.5 1904.95   286.8 1882.92
   299.8 1873.78   329.2 1850.43   348.7 1832.19     352 1830.63   355.3 1829.85
     365 1829.28   371.6 1830.11   381.4 1831.85  389.911831.713  401.281832.087
   493.21834.789  528.651834.204   554.7  1833.5     607 1834.47   626.6 1835.39
   659.3  1837.7   675.6 1838.11   685.5 1840.54   708.3 1843.88   737.8 1845.17
#Mann= 7 ,-1 , 0
       0     .12       0   355.3    .045       0   371.6     .12       0
  389.91     .06       0  401.28     .08       0   493.2     .06       0
  528.65     .08       0
#XS Ineff= 2 , 0
                          501.44         1841.91
Permanent Ineff=
       F       F
Bank Sta=355.3,371.6
XS Rating Curve= 0 ,0
Exp/Cntr=0.3,0.1