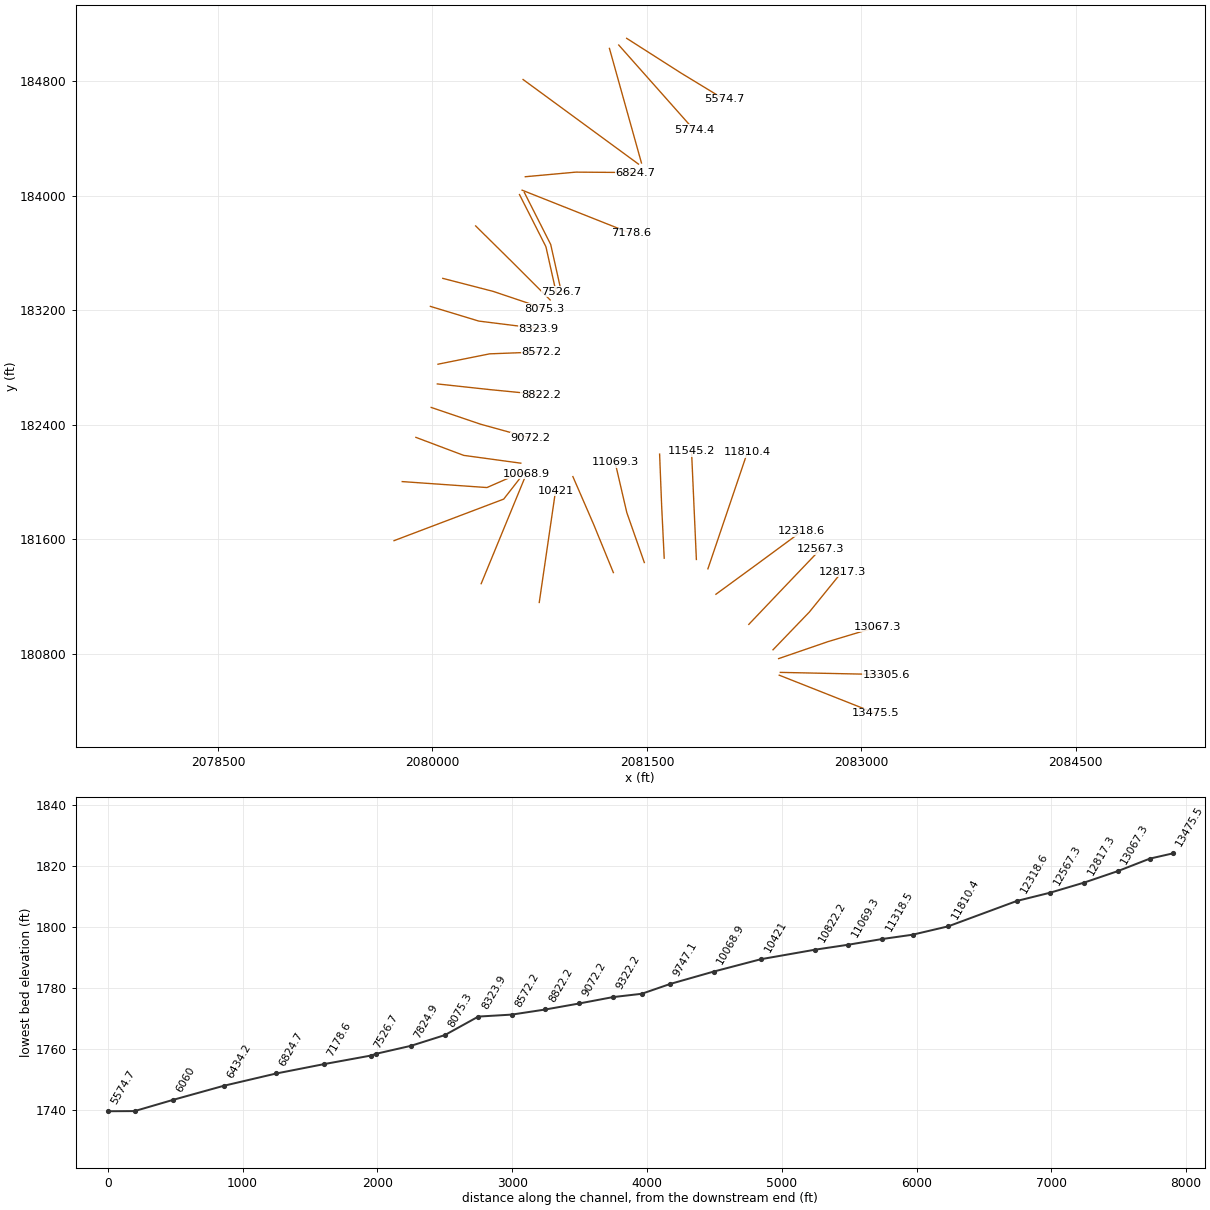
HEC-RAS study RCKCMPCK.prj: RCKCMPCK

--- RCKCMPCK.g01 (geometry) --- (continued)

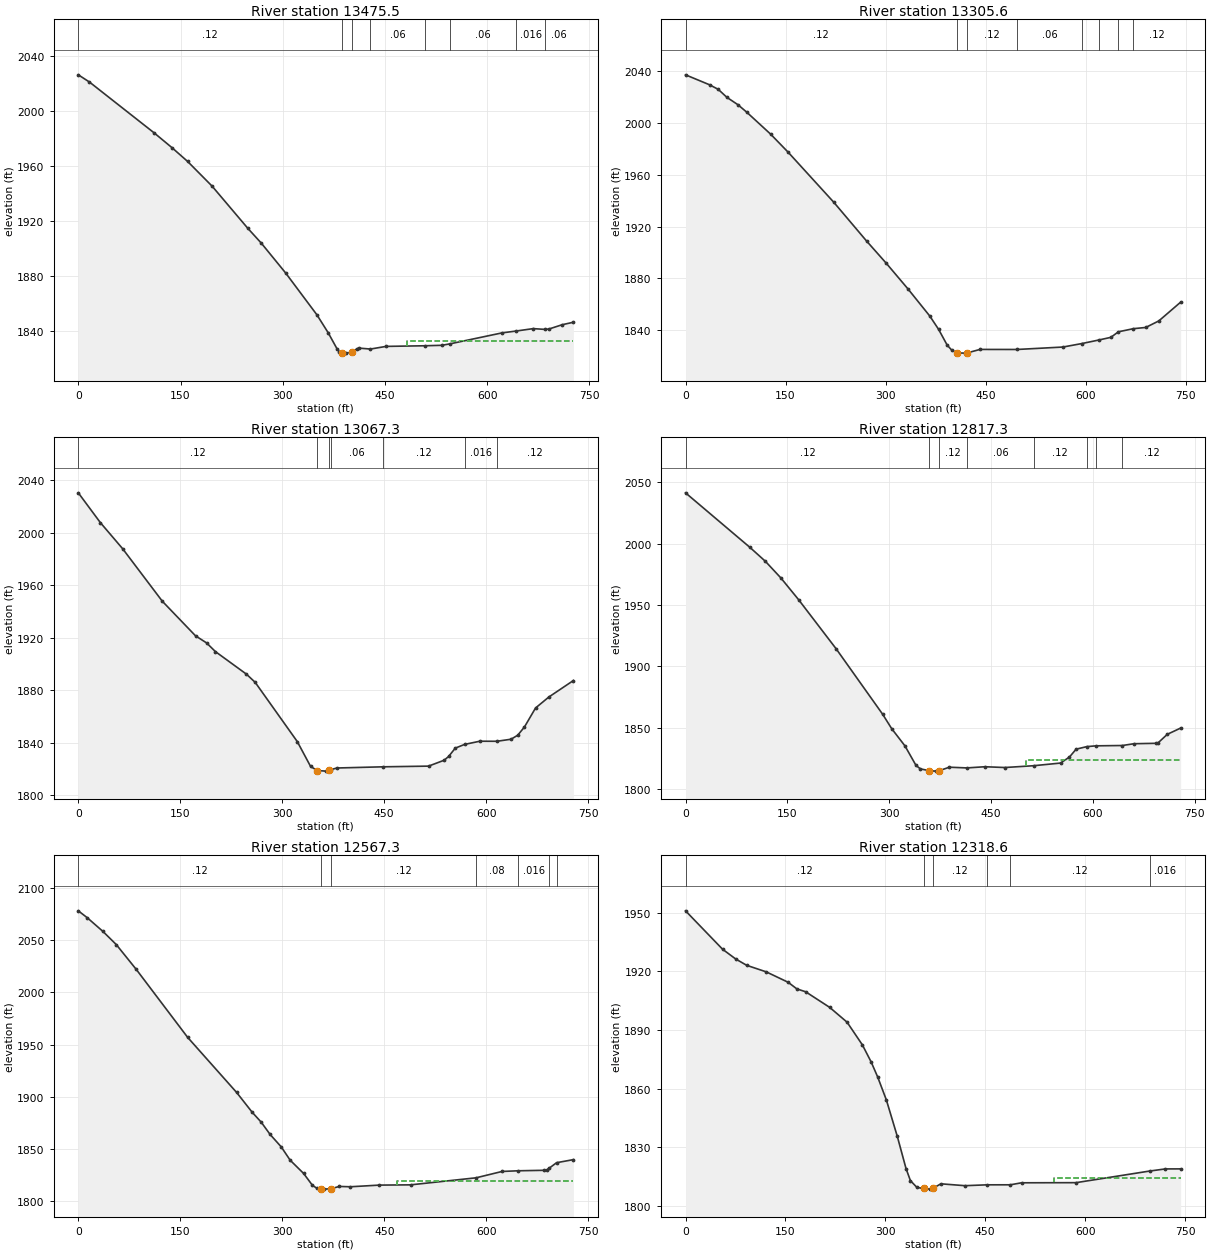
Type RM Length L Ch R = 1 ,13475.5 ,162.1,169.9,177.6
XS GIS Cut Line= 2
     2082425.405      180649.222     2083101.186      180382.295
#Sta/Elev= 30
       0 2026.13    16.4 2020.89   111.3 1984.01   137.5 1973.26   160.4 1963.29
   196.4 1945.32   248.7 1914.78   268.4 1904.08   304.4 1882.26   350.2 1851.94
   366.6 1839.04   379.7 1827.29   382.9  1825.1   386.8 1824.37   392.8 1824.17
   401.8 1824.98   409.1 1827.37   412.4 1827.79  428.77 1827.13   451.7 1829.06
  508.231829.507   533.5 1829.85  545.621830.922   621.8 1838.86  642.571840.205
   667.7 1841.96  684.781841.385   690.6 1841.66   710.2  1844.8   726.6 1846.59
#Mann= 8 ,-1 , 0
       0     .12       0   386.8    .045       0   401.8     .12       0
  428.77     .06       0  508.23     .12       0  545.62     .06       0
  642.57    .016       0  684.78     .06       0
#XS Ineff= 2 , 0
                          482.67          1833.2
Permanent Ineff=
       F       F
Bank Sta=386.8,401.8
XS Rating Curve= 0 ,0
Exp/Cntr=0.3,0.1

Type RM Length L Ch R = 1 ,13305.6 ,229.7,238.3,245.3
XS GIS Cut Line= 2
     2082433.217      180668.754     2083175.405      180653.129
#Sta/Elev= 30
       0 2036.99      36 2029.32      49 2025.81    62.1  2019.6    78.5 2013.97
    91.6 2008.28   127.5 1991.31   153.7 1977.43   222.4  1938.7   271.4 1908.91
   300.9  1891.8   333.6 1871.92   366.3 1851.01   379.4 1840.83   392.4 1828.56
     399 1824.86   406.7 1822.65   418.6 1822.46   421.7 1822.54   441.5 1825.31
   496.91825.273   565.8 1827.15  594.16 1829.83  619.491832.553   637.7 1834.62
  649.031838.896  671.471841.302     690 1842.24   709.6 1847.27   742.4 1861.76
#Mann= 8 ,-1 , 0
       0     .12       0   406.7    .045       0   421.7     .12       0
   496.9     .06       0  594.16     .12       0  619.49     .08       0
  649.03    .016       0  671.47     .12       0
Bank Sta=406.7,421.7
XS Rating Curve= 0 ,0
Exp/Cntr=0.3,0.1

Type RM Length L Ch R = 1 ,13067.3 ,239,250,263.1
XS GIS Cut Line= 3
     2082421.304      180764.964     2082765.869      180883.386
     2083114.459      180987.962
#Sta/Elev= 30
       0 2030.25    32.5 2007.54    65.1 1987.77   123.6  1947.7   172.4 1921.39
   188.7 1915.97   201.7 1909.36   247.2 1892.23   260.2 1885.95   322.1 1840.86
   341.6 1822.01   351.3  1818.8   364.4 1818.35  369.441818.997  371.31  1819.5
   380.7 1820.74  448.451821.636   515.2 1822.16   538.1 1826.64   544.7 1829.49
   554.5 1835.86  568.231838.698   590.6 1841.12  615.73 1841.08   636.5 1842.63
   646.3 1845.66   656.2 1851.92   672.6 1866.43   692.2  1874.8   728.3 1887.35
#Mann= 7 ,-1 , 0
       0     .12       0   351.3    .045       0  369.44     .12       0
  371.31     .06       0  448.45     .12       0  568.23    .016       0
  615.73     .12       0
Bank Sta=351.3,369.44
XS Rating Curve= 0 ,0
Exp/Cntr=0.3,0.1

Type RM Length L Ch R = 1 ,12817.3 ,247.7,250,246
XS GIS Cut Line= 3
     2082382.143      180826.791     2082635.789      181090.086
     2082865.021      181372.475
#Sta/Elev= 30
       0 2041.49    94.7 1997.08   117.5 1985.72   140.4 1972.11   166.5  1954.4
     222 1914.21   290.5 1860.84   303.6 1849.24   323.2 1835.16   339.5 1819.23
     346  1816.4   359.1 1814.95   368.9 1814.58   373.1 1814.81   388.5 1817.78
  414.431817.198     441 1818.16   470.4 1817.52  512.97    1819   552.4 1821.16
   565.5 1826.07   575.3 1832.47  591.151834.572  605.011835.208   643.31835.464
   660.5 1836.92   693.3 1837.27   696.6 1837.91   709.6 1844.58   729.3  1849.7
#Mann= 8 ,-1 , 0
       0     .12       0   359.1    .045       0   373.1     .12       0
  414.43     .06       0  512.97     .12       0  591.15     .08       0
  605.01    .016       0   643.3     .12       0
#XS Ineff= 2 , 0
                          502.12         1823.69
Permanent Ineff=
       F       F
Bank Sta=359.1,373.1
XS Rating Curve= 0 ,0
Exp/Cntr=0.3,0.1

Type RM Length L Ch R = 1 ,12567.3 ,252.4,248.7,244.4
XS GIS Cut Line= 3
       2082212.6      181004.214     2082463.671      181267.786
     2082715.177      181530.902
#Sta/Elev= 30
       0 2078.26    13.1 2071.68    36.1 2058.58    55.8 2045.92    85.3 2022.01
   160.7 1956.94   232.8 1904.02   255.8 1884.92   268.9 1875.57     282 1863.76
   298.4  1851.8   311.5 1839.05   331.2 1826.39   344.3 1814.91   350.9 1812.08
   356.5 1811.41   360.7 1811.29   371.5 1811.63   383.7 1813.87   400.1 1813.56
   442.7 1815.15   488.6 1815.39  584.821822.145   623.1 1828.25  646.481828.883
   685.4 1829.36   688.6 1829.69  692.511831.446  703.211836.638     728 1839.59
#Mann= 7 ,-1 , 0
       0     .12       0   356.5    .045       0   371.5     .12       0
  584.82     .08       0  646.48    .016       0  692.51     .06       0
  703.21     .12       0
#XS Ineff= 2 , 0
                          468.66            1819
Permanent Ineff=
       F       F
Bank Sta=356.5,371.5
XS Rating Curve= 0 ,0
Exp/Cntr=0.3,0.1

Type RM Length L Ch R = 1 ,12318.6 ,492.6,508.3,521.6
XS GIS Cut Line= 3
      2081982.63      181214.765     2082273.873      181427.445
     2082582.278      181654.337
#Sta/Elev= 30
       0 1950.99    55.7 1931.31    75.4 1926.33    91.8 1923.11   121.3 1919.74
   154.1 1914.42   167.2 1911.03   180.3 1909.58   216.4 1901.59   242.6 1893.99
   265.6 1882.36   278.7 1873.67   288.5 1865.99   301.6 1854.19     318 1835.56
   331.1  1819.1   337.7  1812.9   347.5 1809.43   357.4 1808.92   367.2 1808.56
  371.811809.043   383.5 1811.28   419.5 1810.32  453.061810.765  487.691810.772
   504.6  1811.8   586.4 1811.87  697.331817.835   720.6  1818.9   743.5 1818.92
#Mann= 6 ,-1 , 0
       0     .12       0   357.4    .045       0  371.81     .12       0
  453.06     .06       0  487.69     .12       0  697.33    .016       0
#XS Ineff= 2 , 0
                          553.62         1814.29
Permanent Ineff=
       F       F
Bank Sta=357.4,371.81
XS Rating Curve= 0 ,0
Exp/Cntr=0.3,0.1

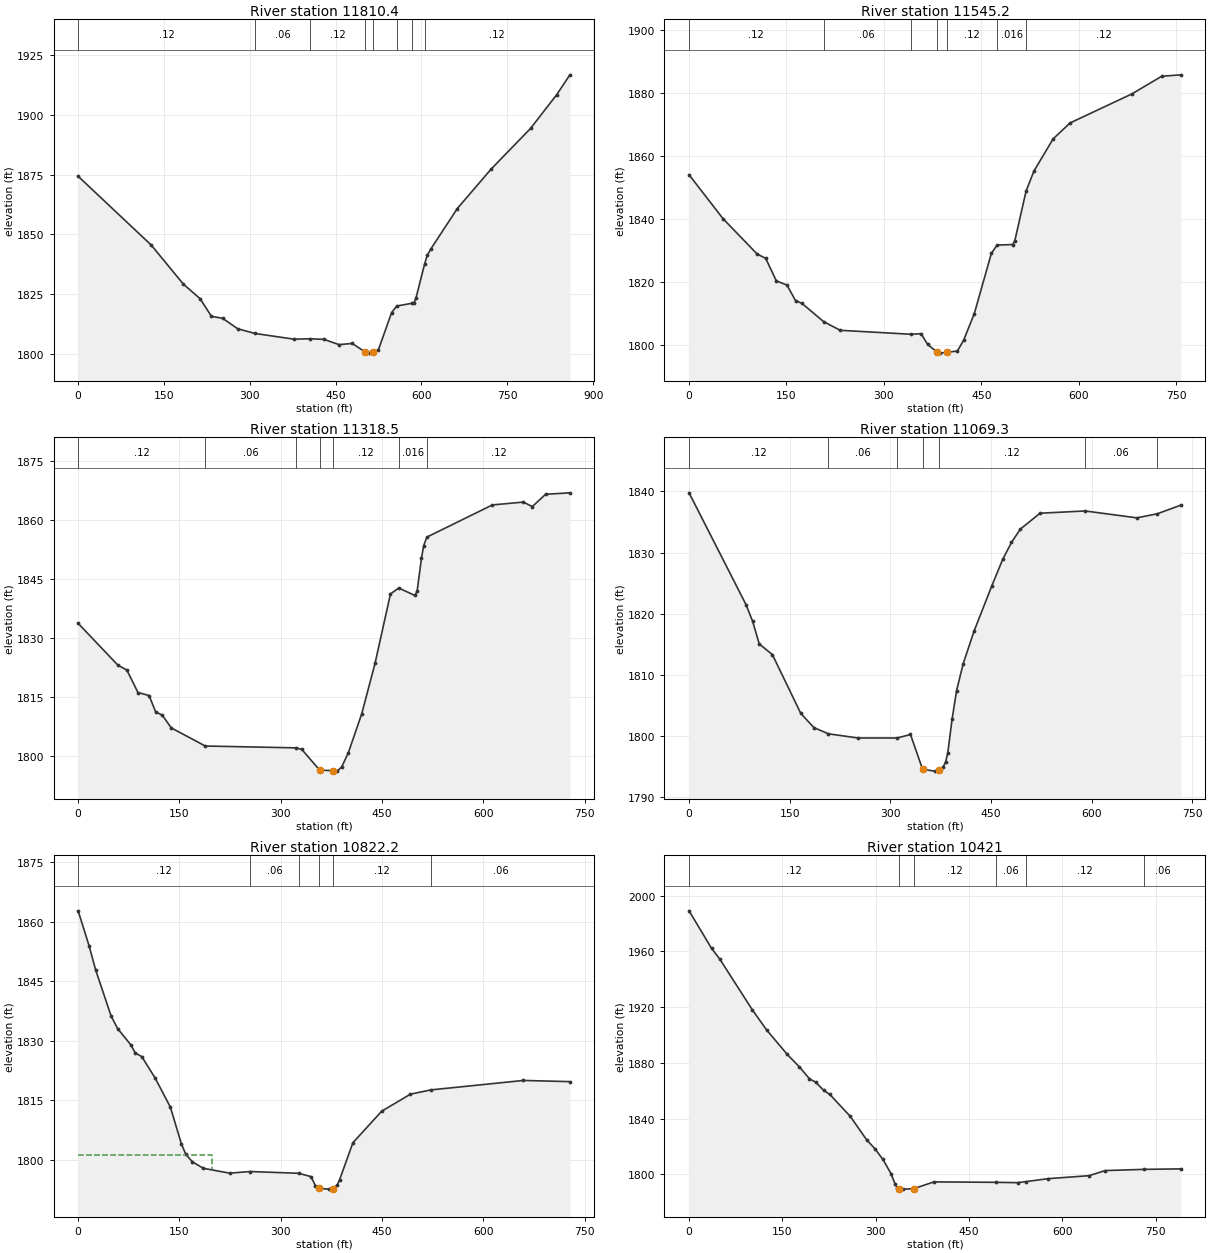
Type RM Length L Ch R = 1 ,11810.4 ,256.6,265.2,273.5
XS GIS Cut Line= 2
     2081926.707      181392.712     2082202.748      182206.514
#Sta/Elev= 30
       0 1874.28   127.9 1845.44   183.7 1829.17   213.2 1823.01   232.9 1815.65
   252.6 1814.81   278.8 1810.45  308.87 1808.48   377.2 1806.08   405.41806.261
   429.7 1805.99   455.9  1803.8   478.9 1804.29   501.8 1800.68   508.4 1800.24
     515 1800.64   524.8 1801.68   547.8 1817.21  556.751819.968  582.721821.071
   587.1 1821.38   590.4 1823.31  605.611837.705   610.1 1841.23   616.6 1843.94
   662.6 1860.77   721.6 1877.26   790.5 1894.29   836.4 1908.46   859.3 1916.74
#Mann= 8 ,-1 , 0
       0     .12       0  308.87     .06       0   405.4     .12       0
   501.8    .045       0     515     .12       0  556.75    .016       0
  582.72     .08       0  605.61     .12       0
Bank Sta=501.8,515
XS Rating Curve= 0 ,0
Exp/Cntr=0.3,0.1

Type RM Length L Ch R = 1 ,11545.2 ,226.5,226.7,226.5
XS GIS Cut Line= 2
     2081845.977      181457.816     2081812.123      182214.327
#Sta/Elev= 30
       0 1853.98    52.4 1840.05   104.9 1828.86     118  1827.5   134.4 1820.36
   150.8 1819.04   163.9 1814.13   173.8 1813.25  207.081807.479   232.8 1804.71
  341.72 1803.46   357.3 1803.64   367.2  1800.3   381.6 1797.84   386.8 1797.48
   396.6 1797.78   413.1 1798.12   422.9 1801.59   439.3 1810.03   465.5 1829.07
  474.321831.713   498.3 1831.88   501.6 1833.04  519.011848.846   531.1 1855.16
   560.6 1865.35   586.8 1870.41   681.9  1879.6   727.8 1885.19   757.3 1885.65
#Mann= 7 ,-1 , 0
       0     .12       0  207.08     .06       0  341.72     .12       0
   381.6    .045       0   396.6     .12       0  474.32    .016       0
  519.01     .12       0
Bank Sta=381.6,396.6
XS Rating Curve= 0 ,0
Exp/Cntr=0.3,0.1

Type RM Length L Ch R = 1 ,11318.5 ,242.5,249.2,253.9
XS GIS Cut Line= 3
      2081620.94      181466.974     2081603.159      181830.584
     2081588.771      182194.271
#Sta/Elev= 30
       0 1833.63      59 1822.97    72.2 1821.74    88.6 1816.04     105 1815.28
   114.8 1811.11   124.6 1810.29   137.8 1807.06  188.221802.442  322.811801.971
   331.2 1801.58   357.5 1796.31   377.2 1796.18   383.7 1796.06   390.3 1797.16
   400.1 1800.78   419.8  1810.6   439.5 1823.43   462.4  1841.1  474.63  1842.6
   498.5 1840.72   501.8 1841.75   508.3  1850.2   511.6 1853.41  516.37 1855.55
   613.2 1863.72   659.2 1864.45   672.3 1863.29     692 1866.43     728  1866.8
#Mann= 7 ,-1 , 0
       0     .12       0  188.22     .06       0  322.81     .12       0
   357.5    .045       0   377.2     .12       0  474.63    .016       0
  516.37     .12       0
Bank Sta=357.5,377.2
XS Rating Curve= 0 ,0
Exp/Cntr=0.3,0.1

Type RM Length L Ch R = 1 ,11069.3 ,245.5,247.1,250
XS GIS Cut Line= 3
     2081481.786       181436.44     2081359.532        181784.8
      2081276.92      182139.104
#Sta/Elev= 30
       0 1839.78      85 1821.44    94.8 1818.72   104.6 1815.03   124.2 1813.28
   166.6 1803.64   186.2 1801.32  207.78 1800.31   251.6 1799.63  310.081799.623
     330  1800.2  348.061794.509   365.9  1794.2   372.5 1794.42     379 1794.95
   382.3 1795.68   385.6 1797.17   392.1 1802.75   398.7 1807.36   408.5 1811.76
   424.9 1817.16   451.1  1824.5   467.5 1828.89   480.6 1831.66   493.7 1833.83
   523.2 1836.44  590.43 1836.81   667.4 1835.68  697.691836.344     733 1837.76
#Mann= 7 ,-1 , 0
       0     .12       0  207.78     .06       0  310.08     .12       0
  348.06    .045       0   372.5     .12       0  590.43     .06       0
  697.69     .12       0
Bank Sta=348.06,372.5
XS Rating Curve= 0 ,0
Exp/Cntr=0.3,0.1

Type RM Length L Ch R = 1 ,10822.2 ,413.2,401.1,387.3
XS GIS Cut Line= 3
     2081265.321      181366.115     2081127.293      181703.217
     2080982.175      182036.988
#Sta/Elev= 30
       0 1862.76    16.3 1853.89      26 1847.82    48.8 1836.25    58.5 1833.06
    78.1 1828.94    84.6 1826.91    94.3 1825.98   113.8 1820.66   136.6 1813.26
   152.9    1804   159.4 1801.36   169.1 1799.47   185.4 1797.82   224.4  1796.6
   254.81797.007  326.681796.564   344.8 1795.73   351.3 1793.48   356.8 1792.73
   370.8 1792.57   377.4 1792.71   383.9 1793.65   387.2 1794.94   406.9 1804.28
   449.5 1812.22   492.1 1816.52  522.191817.593   659.4 1819.98   728.2 1819.68
#Mann= 6 ,-1 , 0
       0     .12       0   254.8     .06       0  326.68     .12       0
   356.8    .045       0   377.4     .12       0  522.19     .06       0
#XS Ineff= 2 , 0
          198.33 1801.29
Permanent Ineff=
       F       F
Bank Sta=356.8,377.4
XS Rating Curve= 0 ,0
Exp/Cntr=0.3,0.1

Type RM Length L Ch R = 1 ,10421   ,357.6,352.1,346.6
XS GIS Cut Line= 2
     2080746.915      181157.305     2080861.277      181939.481
#Sta/Elev= 30
       0 1989.07    36.1 1962.16    49.2 1954.58   101.7 1918.06   124.6 1903.67
   157.4 1886.31   177.1 1877.24   193.5 1868.62   203.4 1866.18   216.5 1860.24
   226.3 1857.35   259.1 1841.67   285.4 1824.82   298.5 1818.55   311.6 1810.78
   324.7  1800.5   331.3    1793   334.6 1790.35   337.8 1789.56   344.4 1789.45
   360.8 1789.73   393.6 1794.64  492.951794.337   528.1 1794.09  541.881794.855
   577.3 1796.96   642.9 1799.09   669.1 1802.76  731.261803.632   790.5 1803.98
#Mann= 6 ,-1 , 0
       0     .12       0   337.8    .045       0   360.8     .12       0
  492.95     .06       0  541.88     .12       0  731.26     .06       0
Bank Sta=337.8,360.8
XS Rating Curve= 0 ,0
Exp/Cntr=0.3,0.1

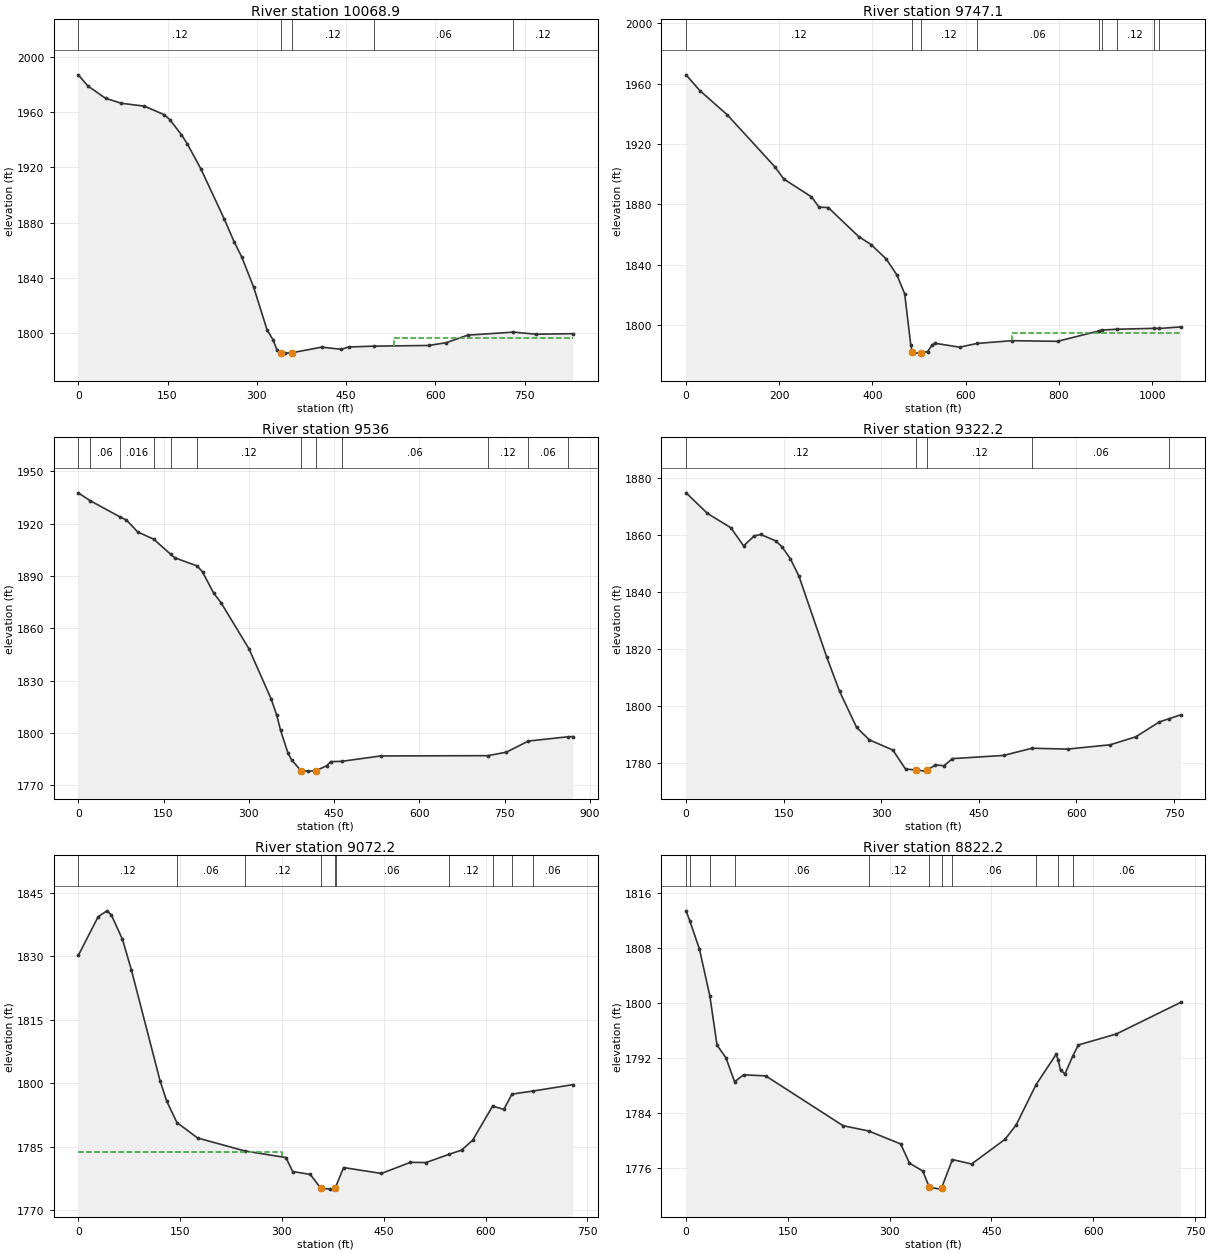
Type RM Length L Ch R = 1 ,10068.9 ,340.4,321.7,303
XS GIS Cut Line= 2
     2080340.769      181288.545     2080657.175      182056.775
#Sta/Elev= 30
       0 1987.14    16.4 1978.98    45.8 1970.15      72 1966.55   111.2 1964.41
   143.9 1958.34   153.7 1954.71   173.4 1943.69   183.2  1937.1   206.1 1918.88
   245.3 1882.58   261.7 1866.28   274.8 1854.88   294.4  1833.5   317.3 1802.12
   327.1 1795.14   333.6 1787.93   340.2 1785.72   346.7 1785.37   358.5 1785.61
   408.9 1789.71   441.6 1788.15   454.7 1789.82   496.51790.434   588.8 1790.93
   618.2 1792.92   654.2  1798.4  731.171800.602   768.7 1799.09   830.8 1799.47
#Mann= 5 ,-1 , 0
       0     .12       0   340.2    .045       0   358.5     .12       0
   496.5     .06       0  731.17     .12       0
#XS Ineff= 2 , 0
                          529.93          1796.5
Permanent Ineff=
       F       F
Bank Sta=340.2,358.5
XS Rating Curve= 0 ,0
Exp/Cntr=0.3,0.1

Type RM Length L Ch R = 1 ,9747.1  ,220.8,211.2,201.1
XS GIS Cut Line= 3
     2079731.394      181589.327     2080498.321      181879.691
     2080646.759      182069.795
#Sta/Elev= 30
       0 1965.86    29.5 1955.41    88.6 1939.28   190.2 1904.98   209.9  1896.7
     269 1884.98   285.4 1878.08   305.1 1877.87   370.7 1858.51   396.9 1853.35
   429.7 1843.68   452.7    1833   469.1 1820.64   482.2 1786.61   485.5 1782.09
   488.8 1781.32   504.5 1781.54   518.3 1782.34   528.1 1786.85   534.7 1787.84
   587.2 1785.25  623.641787.709   698.7 1789.58   797.1 1789.15  885.271795.997
  892.031796.634  924.241797.161 1003.961797.749 1015.271797.652  1061.2  1798.7
#Mann= 9 ,-1 , 0
       0     .12       0   485.5    .045       0   504.5     .12       0
  623.64     .06       0  885.27     .12       0  892.03     .06       0
  924.24     .12       0 1003.96     .06       0 1015.27     .12       0
#XS Ineff= 2 , 0
                          699.18         1794.59
Permanent Ineff=
       F       F
Bank Sta=485.5,504.5
XS Rating Curve= 0 ,0
Exp/Cntr=0.3,0.1

Type RM Length L Ch R = 1 ,9536    ,220.4,213.8,212.6
XS GIS Cut Line= 3
     2079788.686      182002.087     2080381.134       181960.42
     2080633.738      182071.097
#Sta/Elev= 30
       0 1937.73   21.041933.205   73.791923.852    84.8 1922.13   104.4 1915.32
  133.011911.066  162.621902.444   169.7 1900.48  209.431895.731   218.6 1892.32
   238.2 1880.19   251.3  1874.6   300.2 1848.27   339.4 1819.38   349.2 1810.02
   355.7 1801.61   368.8 1788.44   375.3 1784.47   391.6 1778.38   404.6 1778.09
   417.7 1778.28   437.3 1781.27   443.8 1783.54  463.031783.701   531.9  1786.8
  720.41 1786.96   752.9 1788.97  791.581795.349  860.481797.777   869.7 1797.92
#Mann= 12 ,-1 , 0
       0     .12       0   21.04     .06       0   73.79    .016       0
  133.01     .06       0  162.62    .016       0  209.43     .12       0
   391.6    .045       0   417.7     .12       0  463.03     .06       0
  720.41     .12       0  791.58     .06       0  860.48     .12       0
Bank Sta=391.6,417.7
XS Rating Curve= 0 ,0
Exp/Cntr=0.3,0.1

Type RM Length L Ch R = 1 ,9322.2  ,248.9,250,246.3
XS GIS Cut Line= 3
     2079884.123       182311.13     2080218.331      182185.343
      2080617.75      182130.798
#Sta/Elev= 30
       0 1874.85    32.8 1867.62    68.8 1862.58    88.4 1856.21   104.8  1859.7
   114.7  1860.2   137.6 1857.99   147.4 1855.89   160.5  1851.6   173.6 1845.48
   216.2 1817.12   235.9 1805.08   262.1 1792.38   281.7    1788   317.8 1784.42
   337.4 1777.71   353.8 1777.43   366.9    1777  370.981777.382   383.3  1779.2
   396.4 1778.87   409.5  1781.4   488.2 1782.52  531.611785.048   586.5 1784.75
   652.1 1786.27   691.4 1789.08   727.4 1794.28  743.061795.475   760.2 1796.78
#Mann= 5 ,-1 , 0
       0     .12       0   353.8    .045       0  370.98     .12       0
  531.61     .06       0  743.06     .12       0
Bank Sta=353.8,370.98
XS Rating Curve= 0 ,0
Exp/Cntr=0.3,0.1

Type RM Length L Ch R = 1 ,9072.2  ,245,250,253.8
XS GIS Cut Line= 3
      2079991.08       182520.38     2080336.345      182403.219
     2080687.136      182306.446
#Sta/Elev= 30
       0 1830.22    29.3  1839.4    42.3 1840.79    48.8  1839.8    65.1 1834.03
    78.1  1826.9   120.4 1800.62   130.2 1795.77  145.34 1790.67   175.8 1787.02
  244.961783.963     306 1782.38   315.8 1779.08   341.8 1778.39   357.1 1775.15
   371.2 1774.91   377.7  1775.1  379.281775.454   390.8 1780.02   446.6 1778.62
   489.2 1781.25   512.1  1781.2  545.851783.133   564.6 1784.14     581 1786.49
  610.38 1794.58   626.9 1793.78  638.871797.409  669.511798.121   728.5 1799.64
#Mann= 10 ,-1 , 0
       0     .12       0  145.34     .06       0  244.96     .12       0
   357.1    .045       0   377.7     .12       0  379.28     .06       0
  545.85     .12       0  610.38    .016       0  638.87     .12       0
  669.51     .06       0
#XS Ineff= 2 , 0
          300.69 1783.78
Permanent Ineff=
       F       F
Bank Sta=357.1,377.7
XS Rating Curve= 0 ,0
Exp/Cntr=0.3,0.1

Type RM Length L Ch R = 1 ,8822.2  ,243,250,252.9
XS GIS Cut Line= 3
     2080034.173      182684.585     2080397.106      182645.388
     2080758.996      182609.745
#Sta/Elev= 30
       0 1813.36    5.341811.953    19.6 1807.83   35.051800.986    45.6 1793.85
    58.7 1792.02   71.491788.541    84.7 1789.54   117.3 1789.39   231.4 1782.15
  268.971781.385   316.2  1779.5   329.2 1776.72   348.8 1775.57   358.5  1773.2
   374.9 1772.94   376.51773.134  392.441777.236   420.7 1776.59   469.9 1780.17
   486.3 1782.25  515.551788.086   545.2 1792.51  548.211791.753   551.8  1790.2
   558.3 1789.68  569.641792.241     578 1793.88   633.7 1795.46   728.7 1800.06
#Mann= 11 ,-1 , 0
       0     .06       0    5.34     .12       0   35.05    .016       0
   71.49     .06       0  268.97     .12       0   358.5    .045       0
   376.5     .12       0  392.44     .06       0  515.55     .12       0
  548.21    .016       0  569.64     .06       0
Bank Sta=358.5,376.5
XS Rating Curve= 0 ,0
Exp/Cntr=0.3,0.1

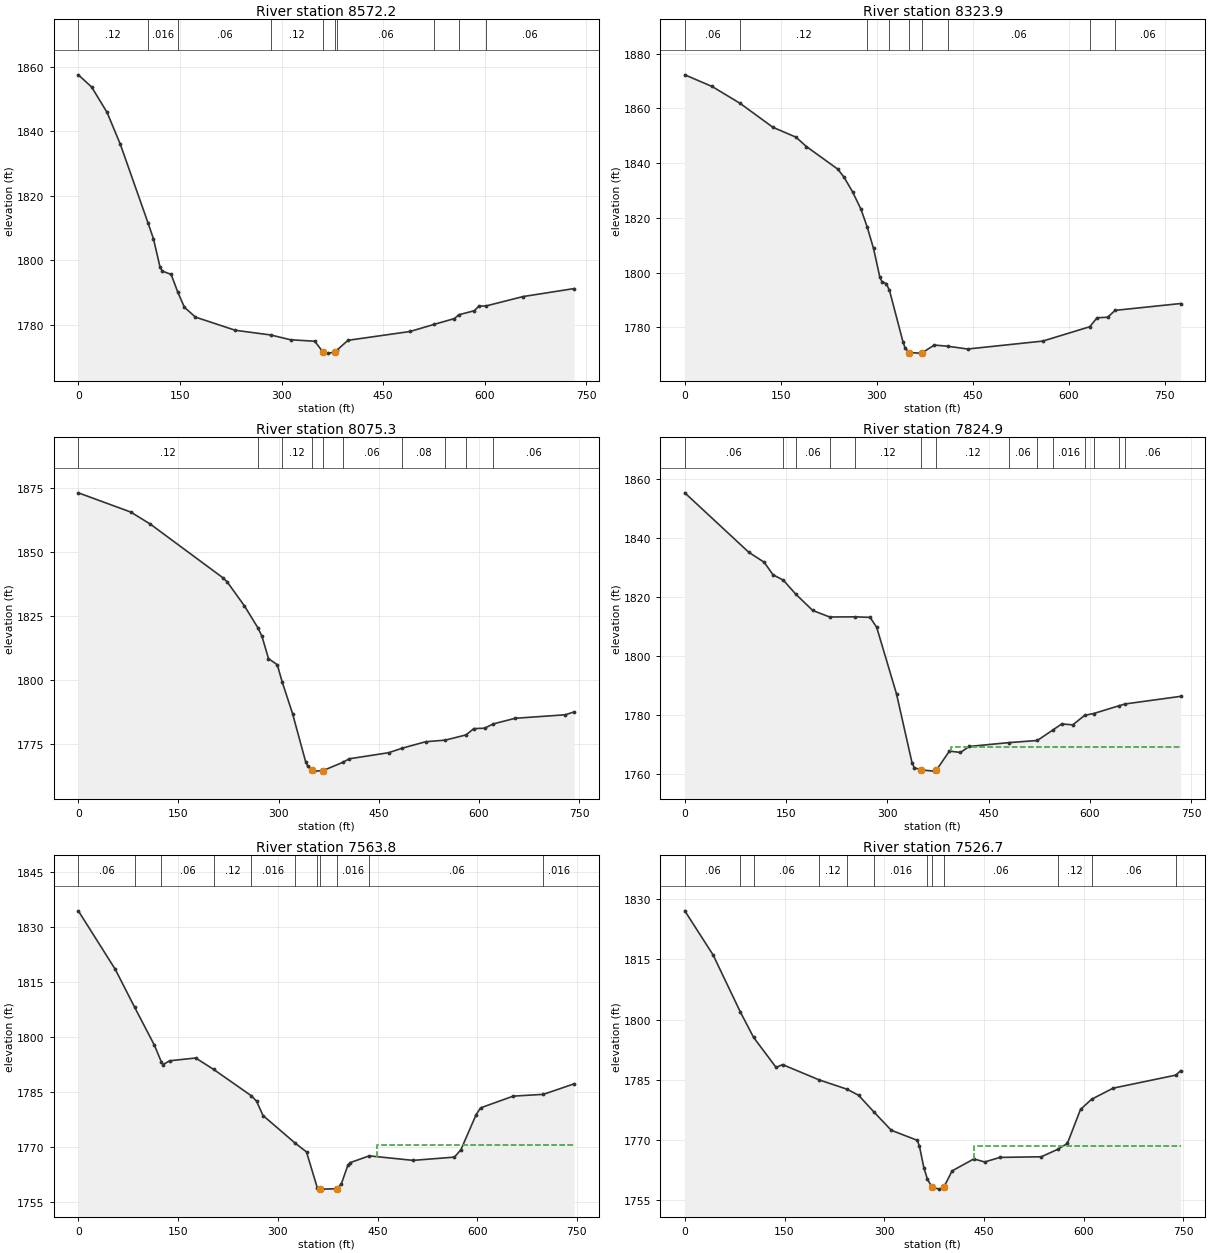
Type RM Length L Ch R = 1 ,8572.2  ,258,248.3,244.1
XS GIS Cut Line= 3
     2080038.775      182822.489     2080400.231      182894.852
     2080763.216      182908.619
#Sta/Elev= 30
       0 1857.43    19.6 1853.67    42.4  1845.8      62 1835.92  103.051811.475
   110.9 1806.67   120.7 1797.82     124 1796.65     137 1795.64  146.891790.092
   156.6 1785.46   172.9 1782.41   231.6 1778.34  284.281776.871   313.2  1775.4
   349.1 1774.94   361.1 1771.58   368.6 1771.26   378.4 1771.55  382.551772.348
   398.1 1775.23   489.7 1777.96   525.61780.192   555.2 1781.96  561.581783.137
   584.6 1784.39   591.2 1785.82  601.621785.865   656.6 1788.78   731.9 1791.25
#Mann= 10 ,-1 , 0
       0     .12       0  103.05    .016       0  146.89     .06       0
  284.28     .12       0   361.1    .045       0   378.4     .12       0
  382.55     .06       0   525.6     .12       0  561.58    .016       0
  601.62     .06       0
Bank Sta=361.1,378.4
XS Rating Curve= 0 ,0
Exp/Cntr=0.3,0.1

Type RM Length L Ch R = 1 ,8323.9  ,248.5,248.6,244
XS GIS Cut Line= 3
     2079985.467      183226.485     2080324.023      183123.785
     2080741.496      183071.781
#Sta/Elev= 30
       0 1872.23    42.6 1867.98   86.341861.822   137.6 1853.08   173.6 1849.47
     190 1846.04   239.1 1837.77     249 1834.74   262.1 1829.49   275.2 1823.15
  284.921816.654   294.8 1808.84   304.6 1798.39   307.9 1796.75   314.5 1796.02
   319.71793.553   340.7 1774.82     344 1772.55   350.5 1770.81   366.7 1770.61
   370.1 1770.63   389.7 1773.56  410.381773.135   441.8 1772.11   559.2 1775.01
  632.591780.248     644 1783.52   660.4 1783.71  672.221786.226   774.5 1788.72
#Mann= 9 ,-1 , 0
       0     .06       0   86.34     .12       0  284.92    .016       0
   319.7     .12       0   350.5    .045       0   370.1     .12       0
  410.38     .06       0  632.59    .016       0  672.22     .06       0
Bank Sta=350.5,370.1
XS Rating Curve= 0 ,0
Exp/Cntr=0.3,0.1

Type RM Length L Ch R = 1 ,8075.3  ,262.1,250.4,239.4
XS GIS Cut Line= 3
     2080072.304      183422.282       2080424.1      183331.485
     2080783.575      183210.703
#Sta/Elev= 30
       0 1873.02    78.6 1865.52     108 1860.79     216 1840.01   222.6 1838.42
   248.8 1828.94  268.83 1820.45     275 1817.12   284.8  1808.4   297.9 1806.02
  305.431799.209   320.8 1786.99   340.4 1768.24   343.7 1766.37   350.2  1764.8
   353.5 1764.53   366.61764.753  395.711767.907   405.8 1769.34   464.7 1771.71
  484.841773.459   520.2 1775.99   549.61776.613  580.771778.658   592.2  1781.1
   608.5 1781.26  621.231782.921   654.3 1785.13   729.5  1786.5   742.6 1787.63
#Mann= 10 ,-1 , 0
       0     .12       0  268.83    .016       0  305.43     .12       0
   350.2    .045       0   366.6     .12       0  395.71     .06       0
  484.84     .08       0   549.6     .12       0  580.77    .016       0
  621.23     .06       0
Bank Sta=350.2,366.6
XS Rating Curve= 0 ,0
Exp/Cntr=0.3,0.1

Type RM Length L Ch R = 1 ,7824.9  ,268.4,261.1,253.9
XS GIS Cut Line= 3
     2080302.038       183788.89      2080560.14      183534.184
     2080823.104      183271.294
#Sta/Elev= 30
       0 1855.17    94.7 1835.08   117.6 1831.68   130.7 1827.44  145.991825.622
  164.311820.903   189.5 1815.37  214.551813.165  252.481813.218   274.4 1813.04
   284.2 1809.69   313.6 1787.12   336.5 1763.93   339.8 1762.24   349.6 1761.43
   369.1 1761.02   372.4 1761.28     392 1767.81   408.3 1767.33   421.3 1769.37
  480.361770.674  522.141771.384  545.231774.943   558.3 1776.99   574.6 1776.67
  592.251779.886   605.71780.514  643.551783.169  652.341783.748   734.4 1786.32
#Mann= 14 ,-1 , 0
       0     .06       0  145.99     .12       0  164.31     .06       0
  214.55    .016       0  252.48     .12       0   349.6    .045       0
   372.4     .12       0  480.36     .06       0  522.14     .08       0
  545.23    .016       0  592.25     .12       0   605.7     .06       0
  643.55     .12       0  652.34     .06       0
#XS Ineff= 2 , 0
                          394.85         1769.14
Permanent Ineff=
       F       F
Bank Sta=349.6,372.4
XS Rating Curve= 0 ,0
Exp/Cntr=0.3,0.1

Type RM Length L Ch R = 1 ,7563.8  ,37,37,37
XS GIS Cut Line= 3
     2080608.838      184007.838     2080793.564      183643.459
     2080867.217       183314.38
#Sta/Elev= 30
       0 1834.36    55.6 1818.37    84.81807.994   114.4 1797.68  124.72 1793.18
   127.5 1792.38   137.3 1793.42   176.5 1794.18  203.331791.088  260.081783.883
     268 1782.42   277.8 1778.48  326.311770.913   343.2 1768.54  359.431758.753
   362.8 1758.39     366 1758.38   388.9 1758.48   395.5 1759.77   405.3 1764.84
   408.5 1765.59  437.591767.461   503.5 1766.23   565.7 1767.12   575.5 1769.16
   598.4 1778.73     605 1780.56   654.1 1783.77  699.531784.256   745.8 1787.13
#Mann= 11 ,-1 , 0
       0     .06       0    84.8     .12       0  124.72     .06       0
  203.33     .12       0  260.08    .016       0  326.31     .06       0
  359.43     .12       0   362.8    .045       0   388.9    .016       0
  437.59     .06       0  699.53    .016       0
#XS Ineff= 2 , 0
                          449.15         1770.33
Permanent Ineff=
       F       F
Bank Sta=362.8,388.9
XS Rating Curve= 0 ,0
Exp/Cntr=0.3,0.1

Type RM Length L Ch R = 1 ,7526.7  ,331.4,348.1,364.6
XS GIS Cut Line= 3
     2080642.475      184023.029     2080827.201       183658.65
     2080900.854      183329.571
#Sta/Elev= 30
       0 1827.04    42.5 1816.09   83.681801.836  103.441795.567   137.3 1788.09
   147.1 1788.79  202.211784.978  243.991782.671   261.5 1781.15  284.761776.955
   310.5 1772.46   349.7 1769.95     353 1768.44   359.5 1763.19  364.791760.371
  371.43 1758.35   382.4 1757.81  389.92 1758.36     402 1762.34   434.7 1765.32
   451.1 1764.57     474  1765.7   536.2 1765.86  560.831767.703   575.5 1769.18
   595.2 1777.64  611.981780.178   644.3 1782.93   738.71786.175   745.8 1787.28
#Mann= 12 ,-1 , 0
       0     .06       0   83.68     .12       0  103.44     .06       0
  202.21     .12       0  243.99     .06       0  284.76    .016       0
  364.79     .12       0  371.43    .045       0  389.92     .06       0
  560.83     .12       0  611.98     .06       0   738.7    .016       0
#XS Ineff= 2 , 0
                          435.39         1768.61
Permanent Ineff=
       F       F
Bank Sta=371.43,389.92
XS Rating Curve= 0 ,0
Exp/Cntr=0.3,0.1

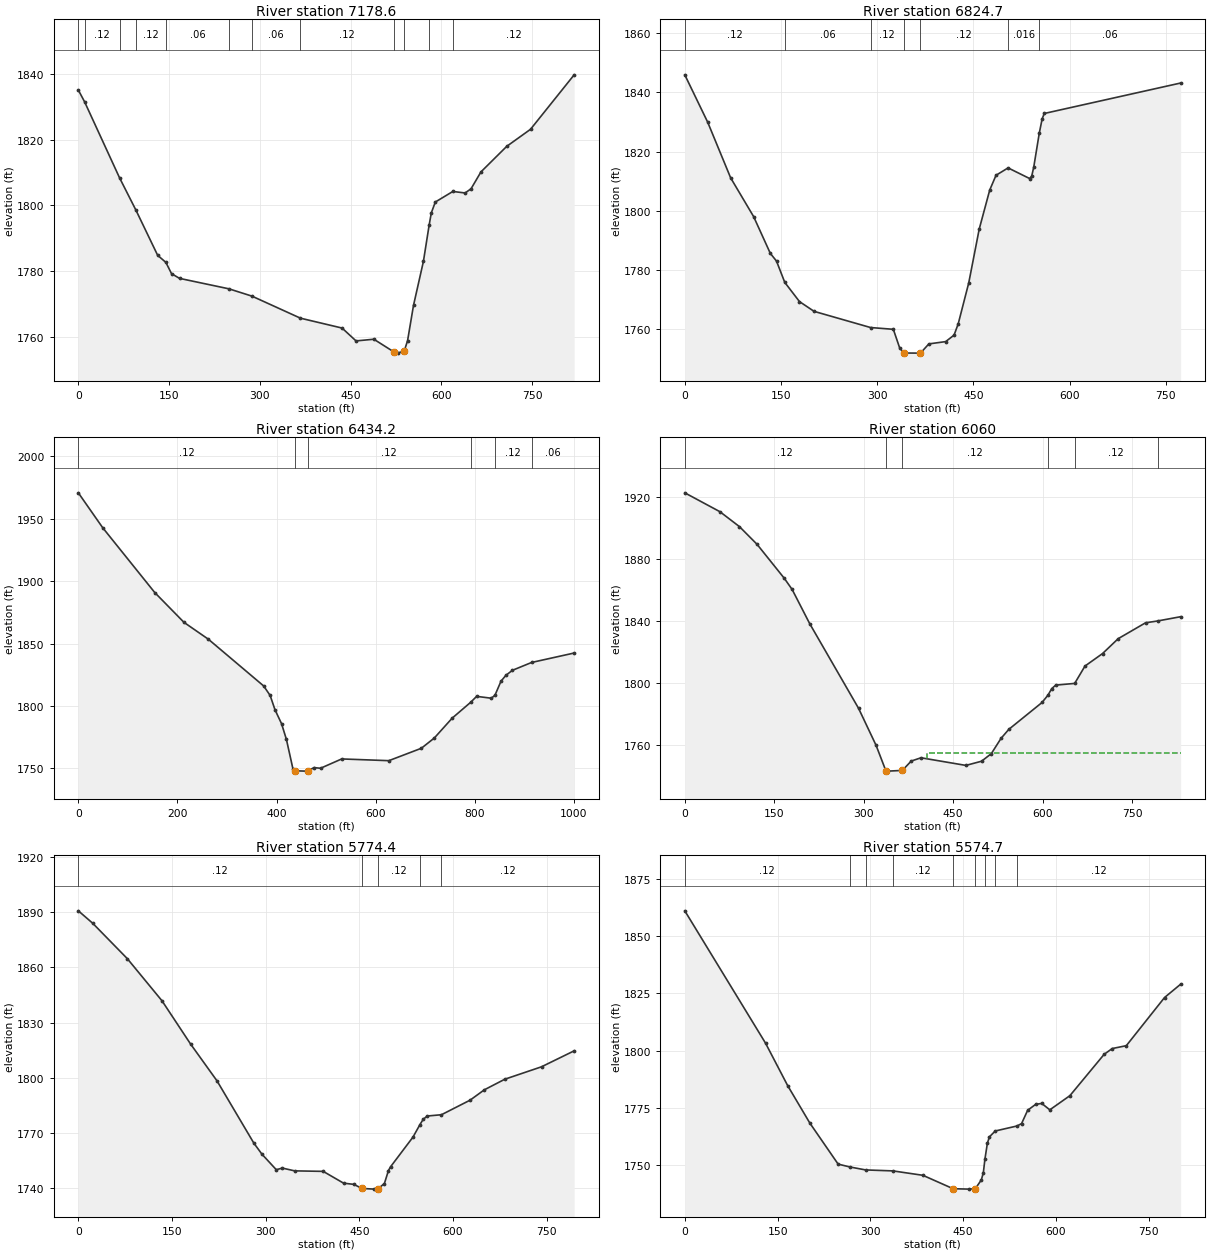
Type RM Length L Ch R = 1 ,7178.6  ,343.3,353.8,361.8
XS GIS Cut Line= 2
     2080627.227      184038.545     2081388.946      183736.462
#Sta/Elev= 30
       0  1835.1   10.381831.499   68.051808.398   95.381798.459   131.1 1784.78
  144.71 1782.62     154  1779.2   167.2 1777.76   248.91774.577  286.931772.352
  367.051765.642   435.9 1762.63   458.9 1758.72   488.4 1759.23   521.2  1755.4
   527.7    1755  538.641755.679   544.1 1758.78   553.9 1769.54   570.3 1782.94
   579.81794.036   583.4 1797.74     590 1801.01  618.921804.221   639.2 1803.76
     649 1805.04   665.4 1810.18     708 1817.96   747.3 1823.15   819.4 1839.73
#Mann= 12 ,-1 , 0
       0     .06       0   10.38     .12       0   68.05     .06       0
   95.38     .12       0  144.71     .06       0   248.9    .016       0
  286.93     .06       0  367.05     .12       0   521.2    .045       0
  538.64     .12       0   579.8    .016       0  618.92     .12       0
Bank Sta=521.2,538.64
XS Rating Curve= 0 ,0
Exp/Cntr=0.3,0.1

Type RM Length L Ch R = 1 ,6824.7  ,406.8,390.6,376.3
XS GIS Cut Line= 3
     2080649.615      184132.612     2081002.526      184164.694
     2081421.105      184161.754
#Sta/Elev= 30
       0 1845.96    35.8  1829.9    71.5 1811.14   107.3 1798.06   133.3 1785.65
     143 1783.02  155.851775.833   178.8 1769.34   201.6 1766.04  289.651760.575
   325.1 1759.98   334.9 1753.74   341.4 1751.97   367.4 1751.93   380.5 1755.05
   406.7 1755.82   419.8 1758.02   426.3 1761.85   442.7 1775.69     459 1793.84
   475.4 1807.04   485.2 1812.02  504.011814.514   537.5 1810.93   540.8 1811.69
     544 1814.76  552.611826.206   557.1 1831.06   560.4  1832.9     773 1843.19
#Mann= 7 ,-1 , 0
       0     .12       0  155.85     .06       0  289.65     .12       0
   341.4    .045       0   367.4     .12       0  504.01    .016       0
  552.61     .06       0
Bank Sta=341.4,367.4
XS Rating Curve= 0 ,0
Exp/Cntr=0.3,0.1

Type RM Length L Ch R = 1 ,6434.2  ,389.1,374.2,359.2
XS GIS Cut Line= 2
     2080633.738      184811.983      2081441.03      184220.837
#Sta/Elev= 30
       0 1970.67    49.2 1942.72   154.2 1890.86   213.2 1866.98   262.4 1853.48
     374 1816.06   387.1 1808.44     397 1796.86   410.1 1785.87   419.9  1773.3
     433 1749.84   436.3 1748.15   459.3 1747.88   462.6 1748.05   475.7 1750.68
   488.8 1750.18   531.5 1757.64   626.6 1756.25   692.2 1766.17   718.4 1774.39
   754.5 1790.32  791.491802.899   803.8 1807.73   833.3 1806.25  840.741808.594
     853  1819.9   862.8 1824.56   875.9 1828.57  914.681834.865  1000.6 1842.43
#Mann= 6 ,-1 , 0
       0     .12       0   436.3    .045       0   462.6     .12       0
  791.49    .016       0  840.74     .12       0  914.68     .06       0
Bank Sta=436.3,462.6
XS Rating Curve= 0 ,0
Exp/Cntr=0.3,0.1

Type RM Length L Ch R = 1 ,6060    ,274.9,285.5,295.8
XS GIS Cut Line= 2
     2081237.905      185029.431     2081461.863       184228.65
#Sta/Elev= 30
       0 1922.75    58.9 1910.58    91.7 1900.94   121.1 1889.58     167 1867.55
     180 1860.43   209.5 1838.35   291.4 1783.78   320.8  1759.9   337.2 1743.49
   340.5 1743.28   364.8 1743.73   379.7 1749.76   396.1 1751.89   471.4 1746.97
   497.6 1749.66     514 1754.54   530.3 1764.39   543.4 1770.23   599.1 1787.55
  609.09  1792.3   615.4  1796.5     622 1798.74  653.831799.843   671.1 1811.03
   700.6 1819.11   726.8  1828.7   772.6 1838.92  792.771840.101   831.5 1842.86
#Mann= 6 ,-1 , 0
       0     .12       0   337.2    .045       0   364.8     .12       0
  609.09    .016       0  653.83     .12       0  792.77     .06       0
#XS Ineff= 2 , 0
                          405.75         1755.24
Permanent Ineff=
       F       F
Bank Sta=337.2,364.8
XS Rating Curve= 0 ,0
Exp/Cntr=0.3,0.1

Type RM Length L Ch R = 1 ,5774.4  ,193.4,199.7,206.4
XS GIS Cut Line= 2
     2081303.009      185052.868     2081830.352      184459.118
#Sta/Elev= 30
       0 1890.72    22.9 1884.01    78.4 1864.77     134 1841.86   179.7 1818.42
   222.2 1798.33     281 1764.62   294.1 1758.55     317 1750.15   326.8 1751.02
   346.4 1749.51   392.2 1749.23   424.8 1742.83   441.2 1742.18   454.2 1739.97
   473.9 1739.59   480.4 1739.92   490.2 1742.64   496.7  1749.7     500  1751.7
     536 1767.86  547.181774.678   552.3 1777.49   558.8 1779.29  581.56 1779.99
   627.4  1787.9   650.3 1793.53     683 1799.27   741.8 1806.02   794.1 1814.69
#Mann= 5 ,-1 , 0
       0     .12       0   454.2    .045       0   480.4     .12       0
  547.18    .016       0  581.56     .12       0
Bank Sta=454.2,480.4
XS Rating Curve= 0 ,0
Exp/Cntr=0.3,0.1

Type RM Length L Ch R = 1 ,5574.7  ,240.8,250,256
XS GIS Cut Line= 3
     2081358.435      185099.719     2081740.665      184855.839
     2082038.262      184675.021
#Sta/Elev= 30
       0 1861.09   130.5 1803.31   166.4  1784.7   202.2 1768.37   247.9 1750.46
  266.811749.224  292.351747.924  336.421747.502   384.9 1745.58   433.8 1739.72
   459.9 1739.54   469.7 1739.77   479.4 1743.54   482.7  1746.8   485.21752.618
   489.2 1759.61   492.5 1762.38  501.921764.933  537.141767.122   544.5 1768.18
   554.3 1773.98   567.3 1776.58   577.1 1776.97   590.1 1774.17   622.6 1780.36
     678 1798.43     691 1800.94   713.8 1802.19   775.6 1823.22   801.6 1829.03
#Mann= 9 ,-1 , 0
       0     .12       0  266.81    .016       0  292.35     .08       0
  336.42     .12       0   433.8    .045       0   469.7     .06       0
   485.2     .08       0  501.92    .016       0  537.14     .12       0
Bank Sta=433.8,469.7
XS Rating Curve= 0 ,0
Exp/Cntr=0.3,0.1