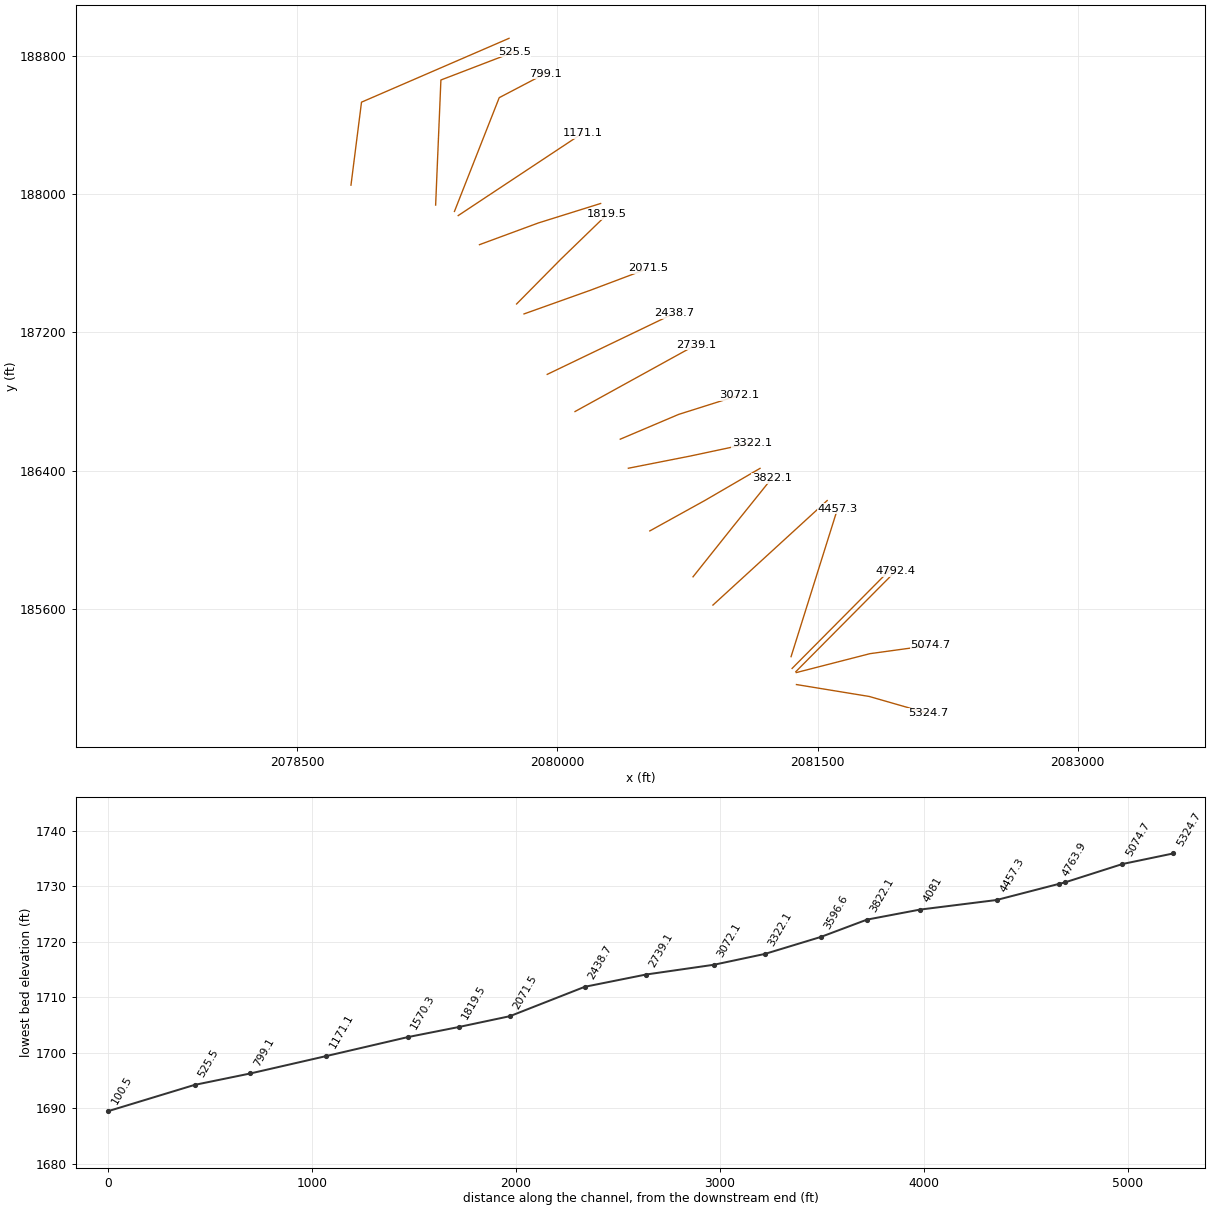
HEC-RAS study RCKCMPCK.prj: RCKCMPCK

--- RCKCMPCK.g01 (geometry) --- (continued)

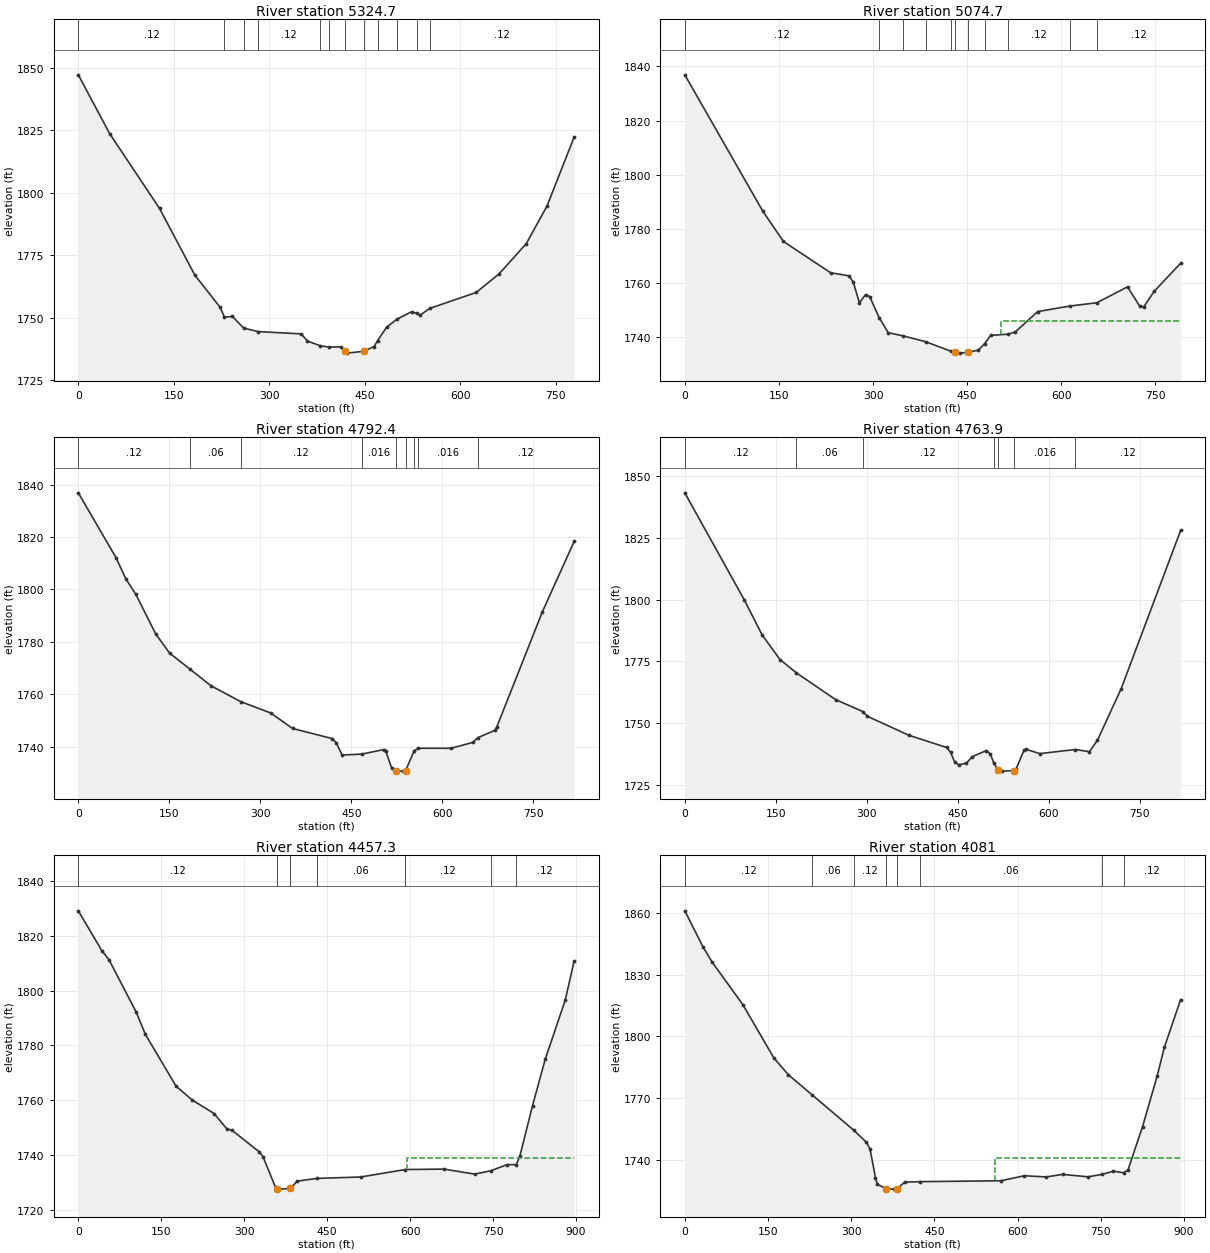
Type RM Length L Ch R = 1 ,5324.7  ,240.5,250,259.3
XS GIS Cut Line= 3
     2081378.323       185165.11     2081798.029      185096.291
     2082137.793      184998.522
#Sta/Elev= 30
       0 1847.23    49.1 1823.75   127.6 1793.78   183.2 1767.04   222.5 1754.34
  229.581750.289   242.1 1750.59  259.51 1745.96  281.991744.537   350.1 1743.61
   359.9 1740.76  378.93 1738.95  393.09 1738.33   412.2  1738.4   418.8 1736.57
     422 1735.91   448.2 1736.64   464.6 1738.55  470.221740.948   484.2 1746.27
  500.961749.552   523.5 1752.46   531.71751.785   536.6 1751.05  552.091753.803
     625 1760.17     661 1767.62   703.6 1779.68   736.3 1794.75   778.9 1822.36
#Mann= 12 ,-1 , 0
       0     .12       0  229.58     .06       0  259.51    .016       0
  281.99     .12       0  378.93     .06       0  393.09     .12       0
   418.8    .045       0   448.2     .12       0  470.22     .08       0
  500.96    .016       0   531.7     .06       0  552.09     .12       0
Bank Sta=418.8,448.2
XS Rating Curve= 0 ,0
Exp/Cntr=0.3,0.1

Type RM Length L Ch R = 1 ,5074.7  ,269.8,282.3,296.9
XS GIS Cut Line= 3
     2081377.604      185234.314     2081802.497      185343.653
     2082150.643      185391.635
#Sta/Elev= 30
       0 1836.92   124.4 1786.46   157.2  1775.3   232.5 1763.71   261.9 1762.58
   268.5 1760.23   278.3 1752.64   288.1 1755.64   294.7  1754.9  309.721747.168
   324.1 1741.56  348.071740.377  383.641738.237   424.31734.698   431.2 1734.29
   438.7    1734   451.8 1734.36     468 1735.12  477.781737.505   487.6 1740.56
     5151741.002   526.6 1741.82   562.4 1749.36  613.631751.414  656.691752.631
   705.6 1758.51   725.1 1751.32   731.6 1751.16   747.9 1756.82   790.2 1767.24
#Mann= 11 ,-1 , 0
       0     .12       0  309.72    .016       0  348.07     .12       0
  383.64     .06       0   424.3     .12       0   431.2    .045       0
   451.8     .12       0  477.78    .016       0     515     .12       0
  613.63     .08       0  656.69     .12       0
#XS Ineff= 2 , 0
                          504.44         1745.74
Permanent Ineff=
       F       F
Bank Sta=431.2,451.8
XS Rating Curve= 0 ,0
Exp/Cntr=0.3,0.1

Type RM Length L Ch R = 1 ,4792.4  ,28.6,28.5,28.7
XS GIS Cut Line= 2
     2081374.963      185239.885      2081950.05      185820.397
#Sta/Elev= 30
       0 1836.83    62.1 1812.11    78.4 1803.99    94.8 1798.09   127.5 1783.02
   150.4  1775.7  184.161769.542     219 1763.19  267.911757.161     317 1752.87
     353 1746.96   418.4  1743.1   424.9 1741.59   434.7 1736.84  466.681737.178
   503.4 1738.91   506.6 1738.36   516.4 1731.82     523 1730.74   535.4 1730.69
   539.3 1730.84  553.381738.448  560.131739.417   614.5  1739.4   650.4 1741.67
   658.21743.435   686.4 1746.23   689.7 1747.59   764.8 1791.49   817.1 1818.31
#Mann= 9 ,-1 , 0
       0     .12       0  184.16     .06       0  267.91     .12       0
  466.68    .016       0     523    .045       0   539.3    .016       0
  553.38     .08       0  560.13    .016       0   658.2     .12       0
Bank Sta=523,539.3
XS Rating Curve= 0 ,0
Exp/Cntr=0.3,0.1

Type RM Length L Ch R = 1 ,4763.9  ,294.6,306.6,316.9
XS GIS Cut Line= 2
     2081353.262      185258.331     2081928.349      185838.843
#Sta/Elev= 30
       0 1843.28    98.1 1799.84   127.5 1785.64   156.9 1775.68  183.831770.291
   248.4 1759.45  293.541754.568   300.7 1752.69   369.4 1744.96   431.4 1740.02
     438 1738.08   444.5 1734.26   451.1 1732.95   464.1 1733.69   473.9 1736.33
   496.8 1738.75   503.4  1737.4  509.181733.824   516.4 1730.69     523 1730.43
   542.6 1730.65   545.8 1731.17   558.9 1738.89   562.2 1739.29   585.1 1737.54
  643.561739.191   666.8 1738.31   679.9 1742.88   719.1 1763.85   817.1 1828.02
#Mann= 7 ,-1 , 0
       0     .12       0  183.83     .06       0  293.54     .12       0
  509.18    .016       0   516.4    .045       0   542.6    .016       0
  643.56     .12       0
Bank Sta=516.4,542.6
XS Rating Curve= 0 ,0
Exp/Cntr=0.3,0.1

Type RM Length L Ch R = 1 ,4457.3  ,387.8,376.3,364.2
XS GIS Cut Line= 2
      2081347.28      185326.306     2081615.509      186181.775
#Sta/Elev= 30
       0 1829.16    42.5 1814.61    55.6 1811.25   104.7 1792.16   121.1 1784.09
   176.7 1765.13   206.1 1760.03   245.4 1755.14   268.3 1749.57   278.1 1748.98
   327.2 1741.12   333.8 1739.41   356.6 1728.14   359.9 1727.62   363.2 1727.52
   382.8 1727.75   395.9 1730.44  431.781731.446   510.4 1731.95  591.231734.678
     661 1734.83   716.6 1733.01  745.781734.214   775.5 1736.48   791.8 1736.44
   798.4 1739.65   821.3 1758.05   844.2 1774.96   880.2 1796.44   896.5 1810.82
#Mann= 7 ,-1 , 0
       0     .12       0   359.9    .045       0   382.8     .12       0
  431.78     .06       0  591.23     .12       0  745.78    .016       0
   791.8     .12       0
#XS Ineff= 2 , 0
                           593.4         1738.85
Permanent Ineff=
       F       F
Bank Sta=359.9,382.8
XS Rating Curve= 0 ,0
Exp/Cntr=0.3,0.1

Type RM Length L Ch R = 1 ,4081    ,255.4,258.9,262.4
XS GIS Cut Line= 2
     2080896.759      185624.483     2081555.613       186228.65
#Sta/Elev= 30
       0 1860.99    32.7 1843.56    49.1 1836.14   104.8 1815.36   160.4  1789.6
   186.6 1781.39   230.21771.428  304.351754.479   327.4 1748.57     334 1745.27
   343.8 1731.28   347.1 1728.12   363.5 1725.98   376.6 1725.79   383.1 1725.94
   396.2 1729.17  424.781729.417   569.8 1729.86   612.3  1732.3   651.6 1731.71
   681.1 1732.95   726.9 1731.77  752.431732.973   772.8 1734.51  791.181733.746
     799 1735.11   825.2  1756.1   851.4 1780.52   864.5 1794.61   893.9 1817.88
#Mann= 8 ,-1 , 0
       0     .12       0   230.2     .06       0  304.35     .12       0
   363.5    .045       0   383.1     .12       0  424.78     .06       0
  752.43    .016       0  791.18     .12       0
#XS Ineff= 2 , 0
                          559.34         1741.08
Permanent Ineff=
       F       F
Bank Sta=363.5,383.1
XS Rating Curve= 0 ,0
Exp/Cntr=0.3,0.1

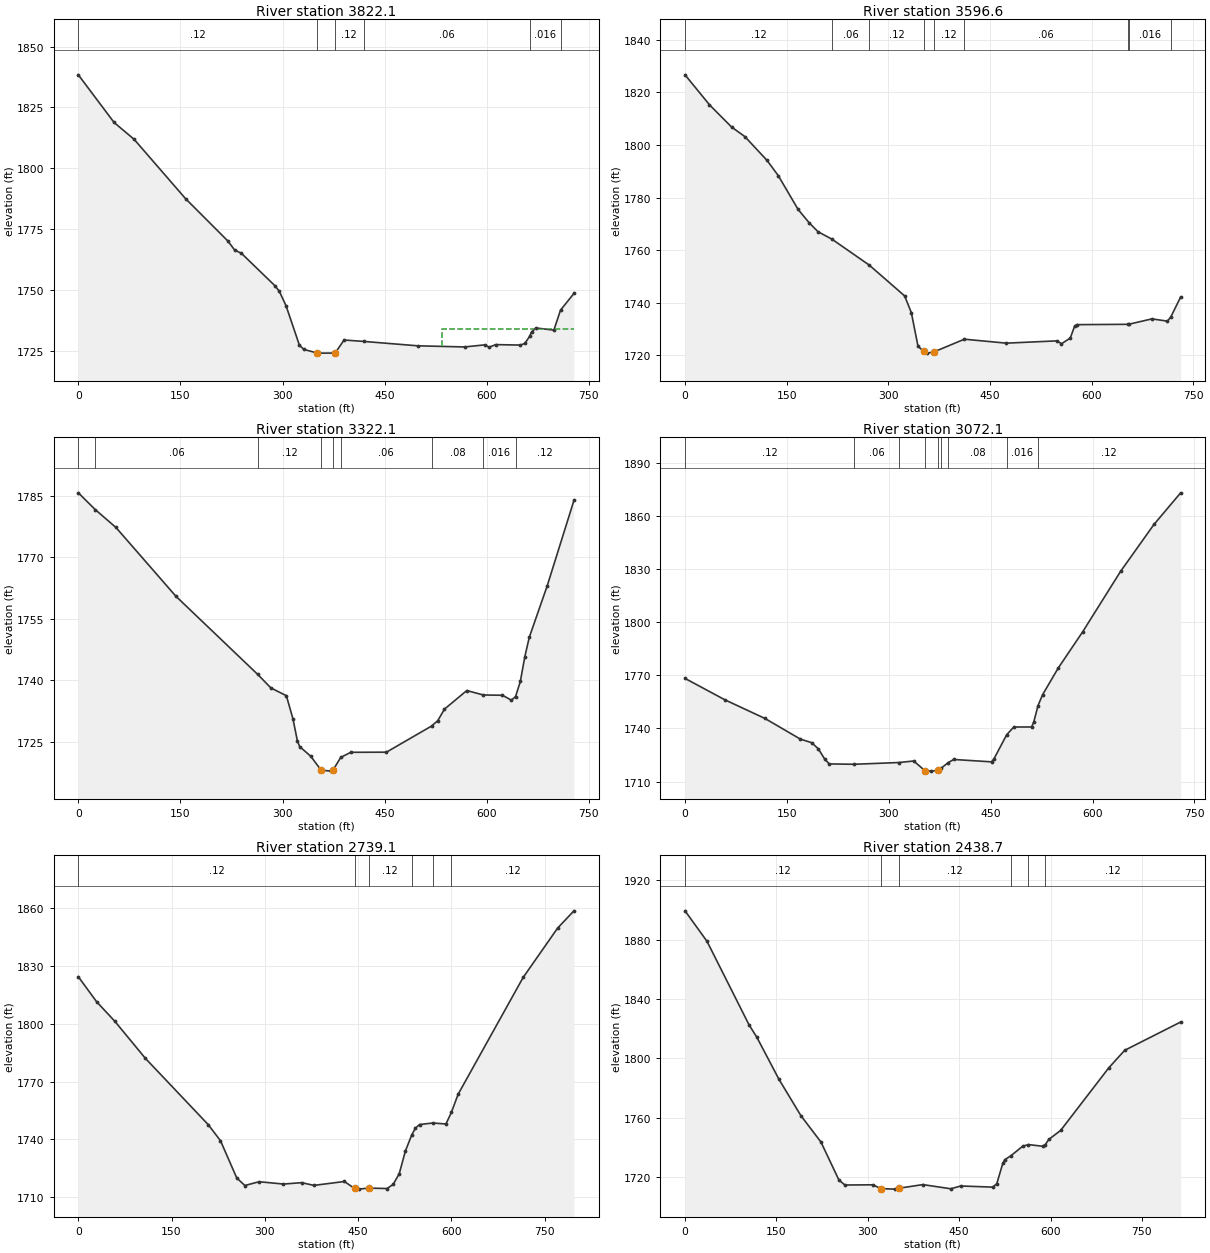
Type RM Length L Ch R = 1 ,3822.1  ,234.4,225.6,217.2
XS GIS Cut Line= 3
     2080782.003      185787.933     2081008.517      186073.067
     2081236.171      186356.992
#Sta/Elev= 30
       0 1838.42    52.5 1818.84      82 1811.89   157.5 1787.52   219.8 1770.07
   229.6 1766.39   239.5 1765.06   288.7 1751.74   295.3 1749.41   305.1 1743.52
   324.8 1727.25   331.4  1725.5     351 1724.04   354.3 1723.99   377.3 1724.02
   390.4 1729.38  419.07 1728.81   498.6    1727   567.4 1726.53   596.9 1727.38
   603.5 1726.42   613.3 1727.49   649.4 1727.31     656 1727.96  662.871730.843
   665.8 1732.69   672.3 1734.33   698.6 1733.44  708.421741.688   728.1 1748.53
#Mann= 6 ,-1 , 0
       0     .12       0     351    .045       0   377.3     .12       0
  419.07     .06       0  662.87    .016       0  708.42     .12       0
#XS Ineff= 2 , 0
                          534.98         1733.78
Permanent Ineff=
       F       F
Bank Sta=351,377.3
XS Rating Curve= 0 ,0
Exp/Cntr=0.3,0.1

Type RM Length L Ch R = 1 ,3596.6  ,281.5,274.4,267.3
XS GIS Cut Line= 3
     2080532.714      186053.102     2080850.498      186229.224
     2081168.235      186414.518
#Sta/Elev= 30
       0 1826.61      36 1815.25    68.7 1806.78    88.4 1803.12   121.1 1794.07
   137.5 1788.34   166.9 1775.45   183.3 1770.35   196.4 1766.97  216.651764.196
  271.861754.309     324 1742.62   333.9 1736.27   343.7 1723.53     352 1721.52
   356.8 1720.88     367 1721.32  412.151726.172     474 1724.67   548.9 1725.54
   555.4 1724.44   568.4 1726.61   574.9 1731.21   578.2  1731.7  653.711731.829
  654.931731.863   688.8 1733.89   711.6 1733.04  716.591734.567   731.2  1742.2
#Mann= 9 ,-1 , 0
       0     .12       0  216.65     .06       0  271.86     .12       0
     352    .045       0     367     .12       0  412.15     .06       0
  653.71     .08       0  654.93    .016       0  716.59     .12       0
Bank Sta=352,367
XS Rating Curve= 0 ,0
Exp/Cntr=0.3,0.1

Type RM Length L Ch R = 1 ,3322.1  ,245.3,250,252.2
XS GIS Cut Line= 3
     2080408.869      186415.293     2080766.166      186485.809
     2081122.117      186561.747
#Sta/Elev= 30
       0 1785.68   24.811781.598    55.3 1777.23   143.1 1760.51  263.691741.387
   282.9 1738.11   305.7 1736.21   315.4 1730.54   321.9 1725.18   325.2  1723.8
   341.4 1721.47   356.7 1718.07   370.8 1717.82     374    1718  385.551721.165
   400.3 1722.41   452.7 1722.44  518.951728.807   528.1 1730.12     538 1732.94
   570.8 1737.47  595.061736.388   623.2 1736.32   636.3 1735.12   642.41735.996
   649.5 1739.71     656 1745.68   662.6 1750.45   688.8 1762.93   728.2 1783.82
#Mann= 9 ,-1 , 0
       0     .12       0   24.81     .06       0  263.69     .12       0
   356.7    .045       0     374     .12       0  385.55     .06       0
  518.95     .08       0  595.06    .016       0   642.4     .12       0
Bank Sta=356.7,374
XS Rating Curve= 0 ,0
Exp/Cntr=0.3,0.1

Type RM Length L Ch R = 1 ,3072.1  ,332.3,333,335.3
XS GIS Cut Line= 3
     2080362.223       186583.27     2080699.052      186726.471
     2081045.708      186836.326
#Sta/Elev= 30
       0 1768.31    58.8 1756.18   117.6 1745.67   169.9 1733.96   186.3 1731.98
   196.1 1728.56   205.9  1722.5   212.4 1719.95  248.851719.745  315.071720.741
   336.6  1721.6   352.9 1716.22   362.7 1715.87   372.6 1716.28  376.831717.432
  387.191720.619   395.5 1722.46   451.2 1721.12   454.5  1722.6  473.551736.465
     484 1740.82   510.2 1740.84   513.4 1743.64  519.641752.932   526.5 1759.18
   549.5 1774.23   585.5 1794.72   641.2 1828.85   690.3 1855.36   729.6 1873.26
#Mann= 9 ,-1 , 0
       0     .12       0  248.85     .06       0  315.07     .12       0
   352.9    .045       0   372.6     .12       0  376.83     .06       0
  387.19     .08       0  473.55    .016       0  519.64     .12       0
Bank Sta=352.9,372.6
XS Rating Curve= 0 ,0
Exp/Cntr=0.3,0.1

Type RM Length L Ch R = 1 ,2739.1  ,299.6,300.4,301.1
XS GIS Cut Line= 2
     2080101.186      186742.972     2080799.102      187128.389
#Sta/Elev= 30
       0 1824.49    29.4 1811.51    58.8 1801.31   107.8 1782.11   209.1 1747.59
   228.7 1739.27   254.9  1719.9   267.9 1715.99   290.8 1717.96     330 1716.75
   359.4 1717.47     379 1716.05     428 1718.08   444.4 1714.46   450.9 1714.11
   467.2 1714.65   496.7 1714.42   506.5 1716.58   516.3 1722.12   526.1 1733.86
  536.591742.444   542.4 1745.83   548.9 1747.68  570.331748.472   591.4 1747.97
  600.12 1753.96     611 1763.42   715.6 1824.12   771.1 1849.78   797.3 1858.74
#Mann= 6 ,-1 , 0
       0     .12       0   444.4    .045       0   467.2     .12       0
  536.59     .08       0  570.33    .016       0  600.12     .12       0
Bank Sta=444.4,467.2
XS Rating Curve= 0 ,0
Exp/Cntr=0.3,0.1

Type RM Length L Ch R = 1 ,2438.7  ,369.4,367.2,364.7
XS GIS Cut Line= 2
      2079941.03      186957.816     2080674.102      187310.681
#Sta/Elev= 30
       0 1899.53    36.1 1878.97     105 1822.73   118.1 1814.15   154.2 1785.94
   190.3 1761.38   223.1 1743.67   252.6 1718.08   262.4 1714.68   308.4 1714.81
   321.5 1712.24   344.5  1711.9     351  1712.5   390.4 1714.95   436.3 1712.14
   452.7 1714.02   505.2 1713.26   511.8 1715.58   521.6  1729.2   524.9 1731.67
  535.121734.478   554.4 1740.83  563.791741.929   587.2  1740.8  591.471741.918
   597.1 1745.38   616.7 1751.52   695.5  1793.6   721.7 1805.48   813.6 1824.56
#Mann= 6 ,-1 , 0
       0     .12       0   321.5    .045       0     351     .12       0
  535.12     .08       0  563.79    .016       0  591.47     .12       0
Bank Sta=321.5,351
XS Rating Curve= 0 ,0
Exp/Cntr=0.3,0.1

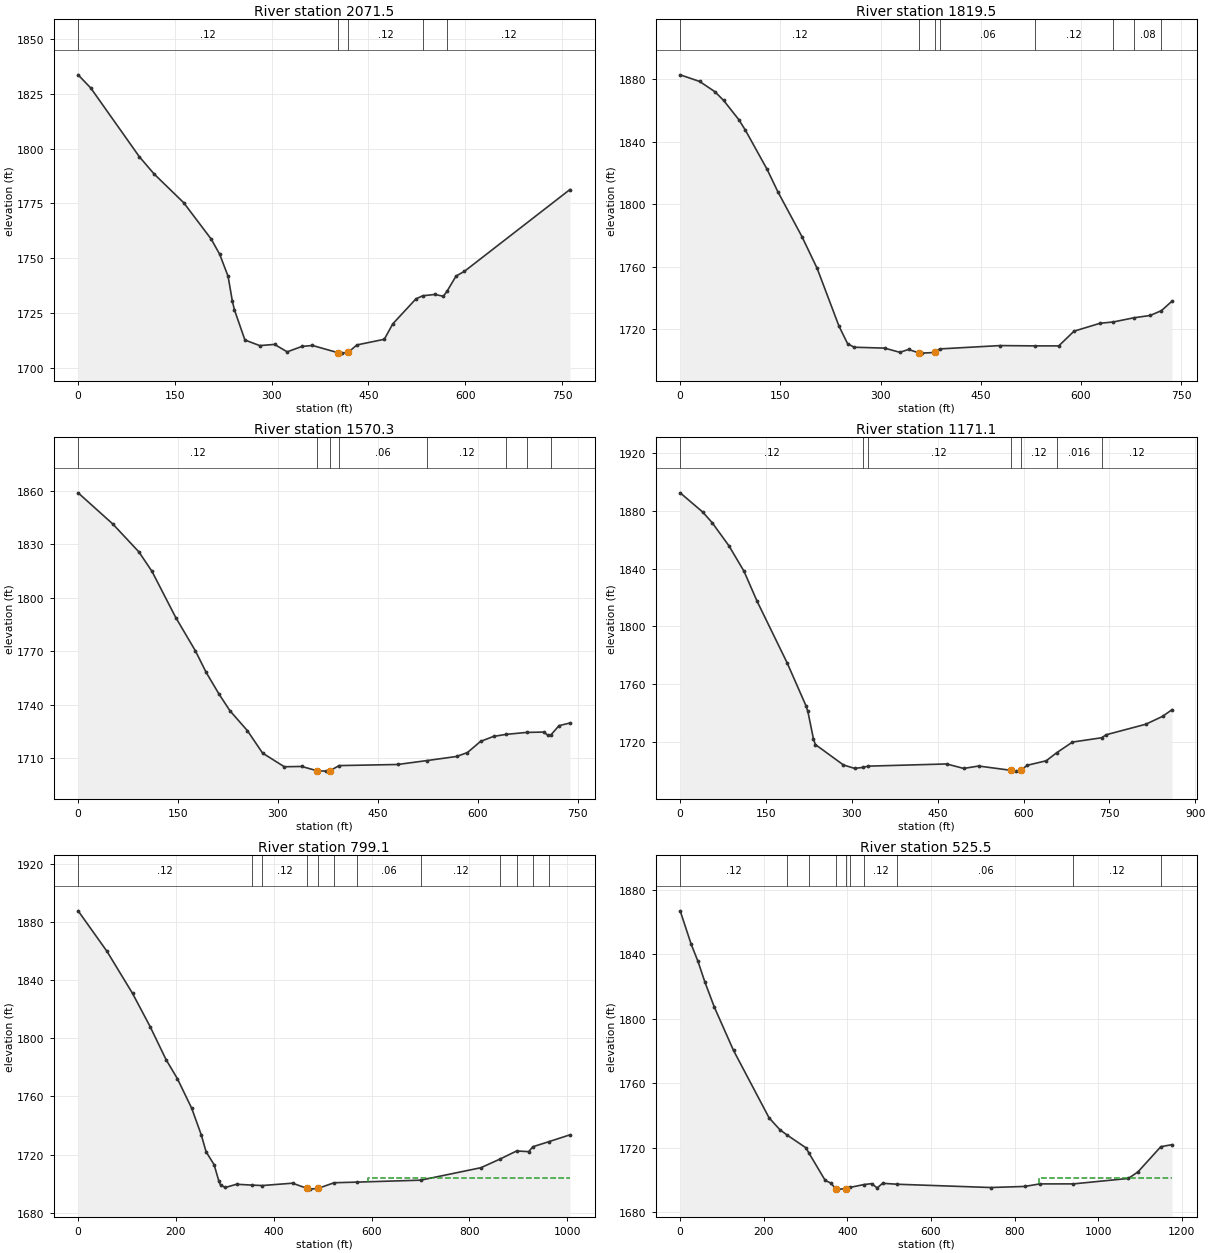
Type RM Length L Ch R = 1 ,2071.5  ,241.5,252,260.8
XS GIS Cut Line= 3
     2079807.186      187307.195     2080189.304      187443.784
     2080522.766      187569.742
#Sta/Elev= 30
       0 1833.66    19.6 1827.63    94.9 1796.26   117.8 1788.38   163.6 1775.29
   206.2 1758.68   219.3 1751.79   232.4 1741.69   238.9 1730.54   242.2  1726.4
   258.5 1712.59   281.4 1710.05   304.4 1710.59     324  1707.2   346.9 1709.67
   363.2 1710.11   402.5 1706.82   409.1 1706.61   418.9 1707.05     432 1710.35
   474.5 1712.93   487.6 1719.96   523.5 1731.38  534.071732.794     553  1733.4
     566 1732.56  571.681734.854   585.7 1741.79   598.7 1743.96   762.2  1781.3
#Mann= 5 ,-1 , 0
       0     .12       0   402.5    .045       0   418.9     .12       0
  534.07    .016       0  571.68     .12       0
Bank Sta=402.5,418.9
XS Rating Curve= 0 ,0
Exp/Cntr=0.3,0.1

Type RM Length L Ch R = 1 ,1819.5  ,259.5,249.2,238.7
XS GIS Cut Line= 3
     2079764.125      187364.555     2080020.073       187624.18
     2080286.761       187882.95
#Sta/Elev= 30
       0 1882.81    29.3 1878.54    52.1 1871.96    65.1 1866.39    87.9 1854.03
    97.6 1847.39   130.2 1822.25   146.5 1807.71   182.3 1779.22   205.1 1758.84
   237.6 1722.06   250.6 1710.72   260.4 1708.43     306 1707.86   328.8 1705.18
   341.8 1706.99   357.1 1704.84   361.3 1704.65   380.9 1705.06  388.661707.351
   478.7 1709.48  531.411709.285   566.7 1709.28   589.5 1718.69   628.6 1723.77
  648.631724.623  679.271727.288   703.6 1728.76  720.431731.869   736.2 1737.91
#Mann= 8 ,-1 , 0
       0     .12       0   357.1    .045       0   380.9     .12       0
  388.66     .06       0  531.41     .12       0  648.63    .016       0
  679.27     .08       0  720.43     .12       0
Bank Sta=357.1,380.9
XS Rating Curve= 0 ,0
Exp/Cntr=0.3,0.1

Type RM Length L Ch R = 1 ,1570.3  ,371,399.2,407.3
XS GIS Cut Line= 3
     2079550.138      187707.376     2079889.456      187832.777
     2080248.968      187945.469
#Sta/Elev= 30
       0 1858.75    52.1 1841.28    91.2 1825.68   110.8 1814.81   146.6 1788.89
     176  1770.3   192.3 1758.13   211.8 1745.86   228.1  1736.6   254.2  1725.5
     277 1712.94   309.6 1705.29   335.7 1705.46   358.5 1703.07   371.6 1702.84
   378.1 1703.05  391.841705.943   479.7 1706.56  524.531708.789   568.2 1711.05
   584.5 1713.23   604.2 1719.48   623.8  1722.3  642.451723.415  673.411724.533
   699.2 1724.72   705.8  1722.8  709.671723.028   722.1 1728.32   738.5  1729.8
#Mann= 8 ,-1 , 0
       0     .12       0   358.5    .045       0   378.1     .12       0
  391.84     .06       0  524.53     .12       0  642.45     .08       0
  673.41    .016       0  709.67     .12       0
Bank Sta=358.5,378.1
XS Rating Curve= 0 ,0
Exp/Cntr=0.3,0.1

Type RM Length L Ch R = 1 ,1171.1  ,378.2,372,386.1
XS GIS Cut Line= 2
     2079427.575       187875.64      2080143.72      188350.901
#Sta/Elev= 30
       0 1892.69    39.4 1879.34    55.8 1872.01    85.3 1855.86   111.5 1838.26
   134.5 1817.33     187 1774.55   219.8 1744.87   223.1 1740.95   232.9 1721.82
   236.2 1717.91   285.4 1703.69   305.1 1701.31  319.09 1702.01  328.321702.891
   465.8 1704.41   495.4  1701.3   521.6 1702.97   577.4 1700.02   587.2 1699.43
  595.131700.148   606.9 1703.53   639.7 1706.61  658.091712.241   685.6 1719.61
  736.411722.597   744.7 1724.71   813.6 1731.98   843.1 1737.47   859.5  1742.1
#Mann= 7 ,-1 , 0
       0     .12       0  319.09     .06       0  328.32     .12       0
   577.4    .045       0  595.13     .12       0  658.09    .016       0
  736.41     .12       0
Bank Sta=577.4,595.13
XS Rating Curve= 0 ,0
Exp/Cntr=0.3,0.1

Type RM Length L Ch R = 1 ,799.1   ,265.9,273.6,280.7
XS GIS Cut Line= 3
     2079405.873      187899.512      2079664.12      188557.064
     2079928.877      188695.953
#Sta/Elev= 30
       0 1887.63    58.9  1859.8   111.2 1830.87   147.2 1808.02   179.9 1785.24
   202.8 1772.31   232.2 1751.88   251.8 1733.53   261.6 1721.96     278 1713.09
   287.8 1701.66   291.1 1699.12   300.9 1697.43   323.8 1699.65  354.471699.084
  376.771698.775   438.3 1700.39   467.7 1696.83   474.2  1696.3   490.6 1696.82
  523.36 1700.69  569.411701.112  700.161702.459   823.4 1711.02  863.051717.069
   896.4 1722.53   920.9 1722.07  929.761725.449  963.11 1729.02  1005.4 1733.62
#Mann= 12 ,-1 , 0
       0     .12       0  354.47     .06       0  376.77     .12       0
   467.7    .045       0   490.6    .016       0  523.36     .12       0
  569.41     .06       0  700.16     .12       0  863.05     .08       0
   896.4    .016       0  929.76     .06       0  963.11     .12       0
#XS Ineff= 2 , 0
                          591.77         1704.22
Permanent Ineff=
       F       F
Bank Sta=467.7,490.6
XS Rating Curve= 0 ,0
Exp/Cntr=0.3,0.1

Type RM Length L Ch R = 1 ,525.5   ,450.1,425,399.3
XS GIS Cut Line= 3
     2079297.366      187936.404     2079327.748       188659.06
     2079750.925      188821.821
#Sta/Elev= 30
       0  1866.9    26.2 1846.26    42.6 1835.54    58.9 1822.89    81.8  1807.1
   127.6  1780.3   212.7 1738.47   238.9 1731.01  256.641727.657   301.1 1719.85
   308.11716.612   346.9 1699.68     360 1698.04   372.7 1694.43   376.4 1694.24
     396 1694.41  405.721695.279  440.061697.084   458.2 1697.65   471.3 1694.99
   484.4 1697.86  519.341697.271   742.9 1695.24   824.4 1695.91   860.3 1697.48
   940.91697.492  1072.3 1700.88  1095.2 1704.91 1150.011720.584  1176.7 1721.82
#Mann= 10 ,-1 , 0
       0     .12       0  256.64    .016       0   308.1     .12       0
   372.7    .045       0     396     .12       0  405.72    .016       0
  440.06     .12       0  519.34     .06       0   940.9     .12       0
 1150.01    .016       0
#XS Ineff= 2 , 0
                          858.31         1701.24
Permanent Ineff=
       F       F
Bank Sta=372.7,396
XS Rating Curve= 0 ,0
Exp/Cntr=0.3,0.1

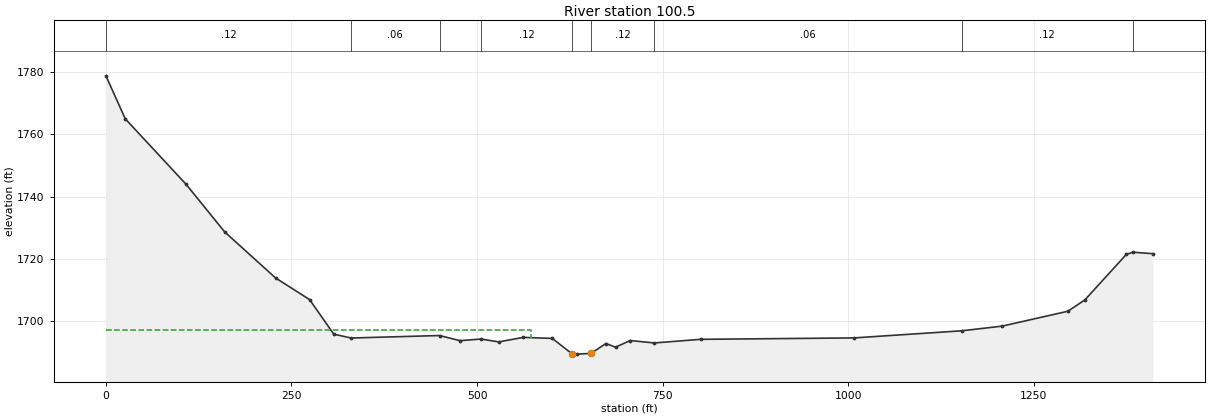
Type RM Length L Ch R = 1 ,100.5   ,97.1,100.5,103.8
XS GIS Cut Line= 3
     2078809.085      188051.422     2078869.849      188531.022
     2079720.543      188899.946
#Sta/Elev= 30
       0 1778.79    26.1 1764.99   107.8 1744.05   160.1 1728.69   228.6 1713.94
   274.4    1707     307 1695.91  330.29 1694.67  449.471695.468   476.9 1693.82
  505.31 1694.34   529.3 1693.42   562.1 1694.87   601.4 1694.54   627.6 1689.65
   634.2  1689.5   653.8 1689.74   673.5  1692.9   686.6 1691.73   706.2 1693.86
  738.811693.088   801.2 1694.25  1007.7  1694.7 1153.281696.989  1207.5 1698.49
    1296 1703.26  1318.9 1706.91  1374.6 1721.47 1383.291722.197  1410.7 1721.72
#Mann= 9 ,-1 , 0
       0     .12       0  330.29     .06       0  449.47    .016       0
  505.31     .12       0   627.6    .045       0   653.8     .12       0
  738.81     .06       0 1153.28     .12       0 1383.29    .016       0
#XS Ineff= 2 , 0
          572.94  1697.1
Permanent Ineff=
       F       F
Bank Sta=627.6,653.8
XS Rating Curve= 0 ,0
Exp/Cntr=0.3,0.1

Chan Stop Cuts=-1
Use User Specified Reach Order=0
Composite Channel Slope=5